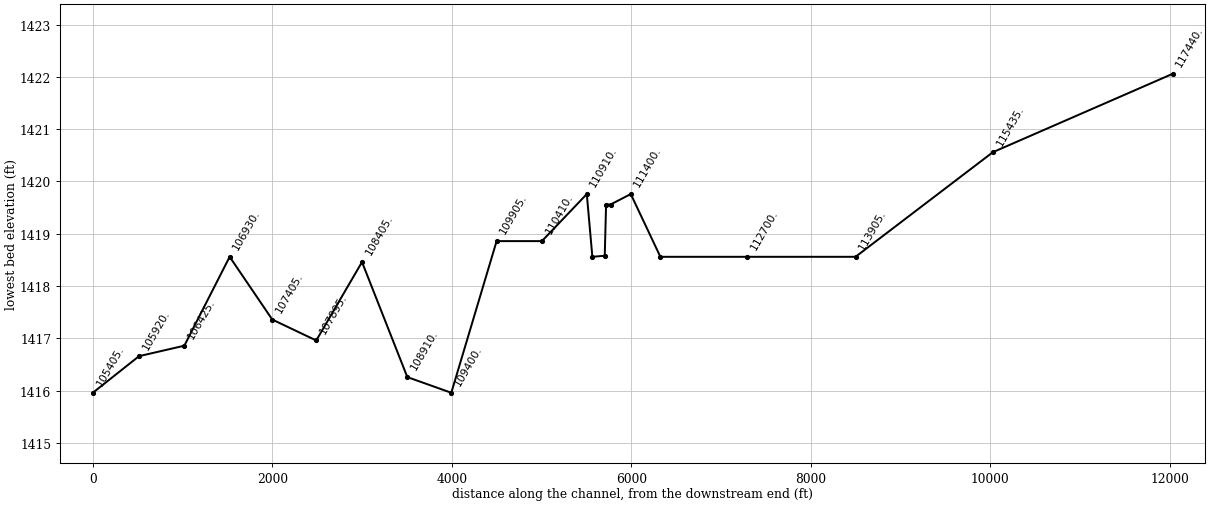
--- RamonaFlowControl.prj (project) ---

Proj Title=Ramona Flow Control Rating Curve
Current Plan=p05
Default Exp/Contr=0.3,0.1
English Units
Geom File=g05
Flow File=f04
Plan File=p05
Y Axis Title=Elevation
X Axis Title(PF)=Main Channel Distance
X Axis Title(XS)=Station
BEGIN DESCRIPTION:
San Jacinto River Alternatives Analysis - Alternative 5
W.O. 03-461  jcc  May 2007
This model is made up of the following Plans:
END DESCRIPTION:
DSS File=..\..\..\..\..\2003\03-0461\hyd\Alternative 5\HEC-RAS\SJRalt5.dss
DSS Export Rating Curves= 0
DSS Export Rating Curve Sorted= 0
DSS Export Volume Flow Curves= 0
DXF Filename=..\..\..\..\..\2003\03-0461\hyd\Alternative 5\HEC-RAS\SJRalt5.
DXF OffsetX= 0
DXF OffsetY= 0
DXF ScaleX= 1
DXF ScaleY= 10

--- RamonaFlowControl.p05 (plan) ---

Plan Title=Ramona Flow Control Curve
Program Version=5.01
Short Identifier=RE Flow Control Curve
Geom File=g05
Flow File=f04
Subcritical Flow
K Sum by GR= 0
Std Step Tol= 0.01
Critical Tol= 0.01
Num of Std Step Trials= 20
Max Error Tol= 0.3
Flow Tol Ratio= 0.001
Split Flow NTrial= 30
Split Flow Tol= 0.02
Split Flow Ratio= 0.02
Log Output Level= 0
Friction Slope Method= 1
Unsteady Friction Slope Method= 2
Unsteady Bridges Friction Slope Method= 1
Parabolic Critical Depth
Global Vel Dist= 0 , 0 , 0
Global Log Level= 0
CheckData=True
Encroach Param=-1 ,0,0, 0
BEGIN DESCRIPTION:
Model to develop rating curve of the Flow Control Structure from the 1974 SJR MDP.  This is taken from the 2000 WEST Model.  Elevations have been updated to NAVD 88.  Results from this model will be input into 2d Ras of Mystic Lake.
JCC  22June2016
END DESCRIPTION:
Computation Interval=1HOUR
Output Interval=1HOUR
Instantaneous Interval=1HOUR
Mapping Interval=1HOUR
Run HTab= 0
Run UNet= 0
Run Sediment= 0
Run PostProcess= 0
Run WQNet= 0
Run RASMapper= 0
UNET Theta= 1
UNET Theta Warmup= 1
UNET ZTol= 0.02
UNET ZSATol= 0.05
UNET MxIter= 20
UNET Max Iter WO Improvement= 0
UNET MaxInSteps= 0
UNET DtIC= 0
UNET DtMin= 0
UNET MaxCRTS= 20
UNET WFStab= 2
UNET SFStab= 1
UNET WFX= 1
UNET SFX= 1
UNET DSS MLevel= 4
UNET Pardiso=0
UNET DZMax Abort= 100
UNET Use Existing IB Tables=-1
UNET Froude Reduction=False
UNET Froude Limit= 1
UNET Froude Power= 10
UNET Time Slicing=0,0, 5
UNET Junction Losses=0
UNET D1 Cores= 0
UNET D2 Coriolis=0
UNET D2 Cores= 0
UNET D2 Theta= 1
UNET D2 Theta Warmup= 1
UNET D2 Z Tol= 0.01
UNET D2 Volume Tol= 0.01
UNET D2 Max Iterations= 20
UNET D2 Equation= 0
UNET D2 RampUpFraction=0.1
UNET D2 TimeSlices= 1
UNET D2 BCVolumeCheck=0
UNET D1D2 MaxIter= 0
UNET D1D2 ZTol=0.01
UNET D1D2 QTol=0.1
UNET D1D2 MinQTol=1
Write IC File= 0
Write IC File at Fixed DateTime=0
Write IC File at Sim End=0
Echo Input=False
Echo Parameters=False
Echo Output=False
Write Detailed= 0
HDF Write Warmup=0
HDF Write Time Slices=0
HDF Flush=0
HDF Face Node Velocities=0
HDF Compression= 1
HDF Chunk Size= 1
HDF Spatial Parts= 1
HDF Use Max Rows=0
HDF Fixed Rows= 1
Calibration Method= 0
Calibration Iterations= 20
Calibration Max Change=0.05
Calibration Tolerance=0.2
Calibration Maximum=1.5
Calibration Minimum=0.5
Calibration Optimization Method= 1
WQ AD Non Conservative
WQ ULTIMATE=-1
WQ Max Comp Step=1HOUR
WQ Output Interval=15MIN
WQ Output Selected Increments= 0
WQ Output face flow=0
WQ Output face velocity=0
WQ Output face area=0
WQ Output face dispersion=0
WQ Output cell volume=0
WQ Output cell surface area=0
WQ Output cell continuity=0
WQ Output cumulative cell continuity=0
WQ Output face conc=0
WQ Output face dconc_dx=0
WQ Output face courant=0
WQ Output face peclet=0
WQ Output face adv mass=0
WQ Output face disp mass=0
WQ Output cell mass=0
WQ Output cell source sink temp=0
WQ Output nsm pathways=0
WQ Output nsm derived pathways=0
WQ Output MaxMinRange=-1
WQ Daily Max Min Mean=-1
WQ Daily Range=0
WQ Daily Time=0
WQ Create Restart=0
WQ Fixed Restart=0
WQ System Summary=0
WQ Write To DSS=0
WQ Use Fixed Temperature=0
Sorting and Armoring Iterations= 10
XS Update Threshold= 0.02
Bed Roughness Predictor= 0
Hydraulics Update Threshold= 0.02
Energy Slope Method= 1
Volume Change Method= 1
Sediment Retention Method= 0
XS Weighting Method= 0
Number of US Weighted Cross Sections= 1
Number of DS Weighted Cross Sections= 1
Upstream XS Weight=0
Main XS Weight=1
Downstream XS Weight=0
Number of DS XS's Weighted with US Boundary= 1
Upstream Boundary Weight= 1
Weight of XSs Associated with US Boundary= 0
Number of US XS's Weighted with DS Boundary= 1
Downstream Boundary Weight= 0.5
Weight of XSs Associated with DS Boundary= 0.5
Percentile Method= 0
Sediment Output Level= 4
Mass or Volume Output= 0
Output Increment Type= 1
Profile and TS Output Increment= 1
XS Output Flag= 0
XS Output Increment= 10
Write Gradation File= 0
Read Gradation Hotstart= 0
Write HDF5 File= 1
Write DSS Sediment File= 0
SV Curve= 0
Specific Gage Flag= 0

--- RamonaFlowControl.f04 (steady flow) ---

Flow Title=Flow Series
Program Version=5.01
Number of Profiles= 14
Profile Names=PF 1,PF 2,PF 3,PF 4,PF 5,PF 6,PF 7,PF 8,PF 9,PF 10,PF 11,PF 12,PF 13,PF 14
River Rch & RM=San Jacinto,4               ,117440.
     250     500    1000    1500    2000    2500    3000    3500    4000    4500
    5000    5500    6000    6500
Boundary for River Rch & Prof#=San Jacinto,4               , 1
Up Type= 0
Dn Type= 2
Boundary for River Rch & Prof#=San Jacinto,4               , 2
Up Type= 0
Dn Type= 2
Boundary for River Rch & Prof#=San Jacinto,4               , 3
Up Type= 0
Dn Type= 2
Boundary for River Rch & Prof#=San Jacinto,4               , 4
Up Type= 0
Dn Type= 2
Boundary for River Rch & Prof#=San Jacinto,4               , 5
Up Type= 0
Dn Type= 2
Boundary for River Rch & Prof#=San Jacinto,4               , 6
Up Type= 0
Dn Type= 2
Boundary for River Rch & Prof#=San Jacinto,4               , 7
Up Type= 0
Dn Type= 2
Boundary for River Rch & Prof#=San Jacinto,4               , 8
Up Type= 0
Dn Type= 2
Boundary for River Rch & Prof#=San Jacinto,4               , 9
Up Type= 0
Dn Type= 2
Boundary for River Rch & Prof#=San Jacinto,4               , 10
Up Type= 0
Dn Type= 2
Boundary for River Rch & Prof#=San Jacinto,4               , 11
Up Type= 0
Dn Type= 2
Boundary for River Rch & Prof#=San Jacinto,4               , 12
Up Type= 0
Dn Type= 2
Boundary for River Rch & Prof#=San Jacinto,4               , 13
Up Type= 0
Dn Type= 2
Boundary for River Rch & Prof#=San Jacinto,4               , 14
Up Type= 0
Dn Type= 2
DSS Import GetInterval= 0
DSS Import GetPeak= 0
DSS Import FillOption= 0

--- RamonaFlowControl.g05 (geometry) ---

Geom Title=RE Flow Control Structure
Program Version=5.01
BEGIN GEOM DESCRIPTION:
This models the Flow Clontrol Structure at Ramona Expressway.  This was from the WEST model.  It was vertically adjusted 2.56 feet to be on NAVD 88.  This models the 7 cell 5'h x 10' Wide Flow Control Structure proposed in the 1974 Master Plan
JCC 22June2016
END GEOM DESCRIPTION:

River Reach=San Jacinto     ,4
Reach XY= 2
        0.465015       0.6505214      -0.0016522       0.1713422

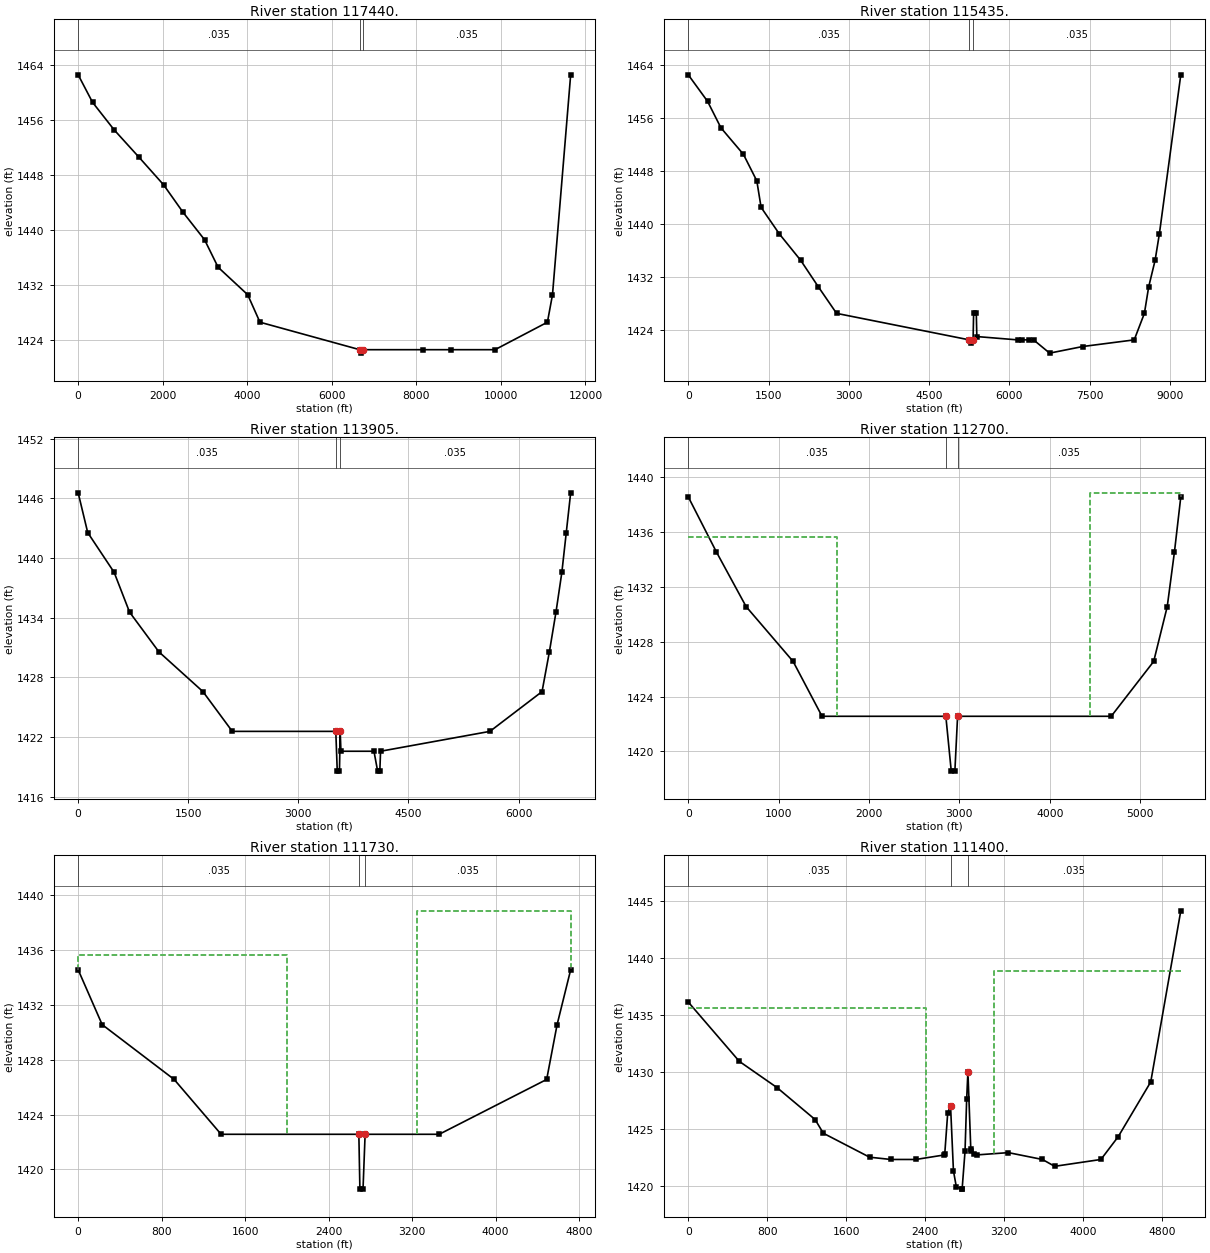
Type RM Length L Ch R = 1 ,117440. ,1950,2005,1950
BEGIN DESCRIPTION:
WEST xsec 7500, beginning reach 4 after reach 2 & 3 rejoin.
END DESCRIPTION:
#Sta/Elev= 19
       0 1462.56     340 1458.56     850 1454.56    1440 1450.56    2020 1446.56
    2480 1442.56    2990 1438.56    3310 1434.56    4010 1430.56    4300 1426.56
    6660 1422.56    6695 1422.06    6730 1422.56    8150 1422.56    8820 1422.56
    9860 1422.56   11100 1426.56   11220 1430.56   11650 1462.56
#Mann= 3 , 0 , 0
       0    .035       0    6660     .04       0    6730    .035       0
Bank Sta=6660,6730
XS Rating Curve= 0 ,0
Exp/Cntr=0.3,0.1

Type RM Length L Ch R = 1 ,115435. ,1800,1530,1580
BEGIN DESCRIPTION:
WEST xsec 7400
END DESCRIPTION:
#Sta/Elev= 28
       0 1462.56     360 1458.56     610 1454.56    1030 1450.56    1280 1446.56
    1360 1442.56    1700 1438.56    2100 1434.56    2430 1430.56    2770 1426.56
    5250 1422.56    5285 1422.06    5320 1422.56    5330 1426.56    5380 1426.56
    5390 1423.06    6150 1422.56    6230 1422.56    6360 1422.56    6450 1422.56
    6750 1420.56    7370 1421.56    8330 1422.56    8520 1426.56    8600 1430.56
    8720 1434.56    8800 1438.56    9200 1462.56
#Mann= 3 , 0 , 0
       0    .035       0    5250     .04       0    5320    .035       0
#XS Ineff= 2 , 0
       0    2550                       0
Permanent Ineff=
       F       F
Bank Sta=5250,5320
XS Rating Curve= 0 ,0
Exp/Cntr=0.3,0.1

Type RM Length L Ch R = 1 ,113905. ,1070,1205,1270
BEGIN DESCRIPTION:
WEST xsec 7300
END DESCRIPTION:
#Sta/Elev= 23
       0 1446.56     130 1442.56     490 1438.56     700 1434.56    1100 1430.56
    1700 1426.56    2100 1422.56    3510 1422.56    3530 1418.56    3560 1418.56
    3570 1422.56    3580 1420.56    4030 1420.56    4080 1418.56    4110 1418.56
    4120 1420.56    5610 1422.56    6320 1426.56    6420 1430.56    6510 1434.56
    6590 1438.56    6650 1442.56    6710 1446.56
#Mann= 3 , 0 , 0
       0    .035       0    3510     .04       0    3570    .035       0
#XS Ineff= 2 , 0
       0    1700                       0
Permanent Ineff=
       F       F
Bank Sta=3510,3570
XS Rating Curve= 0 ,0
Exp/Cntr=0.3,0.1

Type RM Length L Ch R = 1 ,112700. ,810,970,1000
BEGIN DESCRIPTION:
WEST xsec 7200
END DESCRIPTION:
#Sta/Elev= 14
       0 1438.56     310 1434.56     640 1430.56    1160 1426.56    1480 1422.56
    2850 1422.56    2910 1418.56    2950 1418.56    2980 1422.56    4680 1422.56
    5150 1426.56    5300 1430.56    5380 1434.56    5450 1438.56
#Mann= 3 , 0 , 0
       0    .035       0    2850    .035       0    2980    .035       0
#XS Ineff= 2 , 0
       0    1650 1435.61    4450       0 1438.86
Permanent Ineff=
       F       F
Bank Sta=2850,2980
XS Rating Curve= 0 ,0
Exp/Cntr=0.3,0.1

Type RM Length L Ch R = 1 ,111730. ,330,330,330
BEGIN DESCRIPTION:
WEST sta/elev data at RCFCD xsec 71 location
END DESCRIPTION:
#Sta/Elev= 12
       0 1434.56     230 1430.56     920 1426.56    1370 1422.56    2690 1422.56
    2700 1418.56    2730 1418.56    2750 1422.56    3460 1422.56    4490 1426.56
    4590 1430.56    4720 1434.56
#Mann= 3 , 0 , 0
       0    .035       0    2690    .035       0    2750    .035       0
#XS Ineff= 2 , 0
       0    2000 1435.61    3250       0 1438.86
Permanent Ineff=
       F       F
Bank Sta=2690,2750
XS Rating Curve= 0 ,0
Exp/Cntr=0.3,0.1

Type RM Length L Ch R = 1 ,111400. ,225,225,225
BEGIN DESCRIPTION:
This is xsec 7000 (RCFCD data  from xsec 200100 to 207000) modified to U/S face of Ramona Expressway Bridge and adjusted to fit bridge approach.  The updated data comes from RCFC&WCD San Jancinto River map, portion of section T4SR2W,Sheet 5 of 13.  Greater topo detail was avialable from this map for the approach roads to the bridge from both directions. GR data was taken on the center line of the road from the edge of bridge crossing to the outer banks.
END DESCRIPTION:
#Sta/Elev= 30
       0 1436.16   517.1 1430.96   899.1 1428.66  1284.7 1425.86  1367.8 1424.66
  1836.4 1422.56  2052.3 1422.36  2305.1 1422.36  2595.2 1422.76    2598 1422.86
    2628 1426.46  2656.6 1427.06  2685.9 1421.36  2715.2 1419.96  2771.9 1419.76
  2773.8 1419.76  2803.1 1423.06  2819.9 1427.66  2832.4 1430.06  2861.7 1423.26
  2867.9 1423.06    2891 1422.86  2923.2 1422.76  3242.4 1422.96  3587.4 1422.36
  3711.1 1421.76  4179.7 1422.36    4355 1424.36  4684.4 1429.16  4988.8 1444.16
#Mann= 3 , 0 , 0
       0    .035       0  2656.6    .035       0  2832.4    .035       0
#XS Ineff= 2 , 0
       0    2405 1435.61    3095       0 1438.86
Permanent Ineff=
       F       F
Bank Sta=2656.6,2832.4
XS Rating Curve= 0 ,0
Exp/Cntr=0.3,0.1

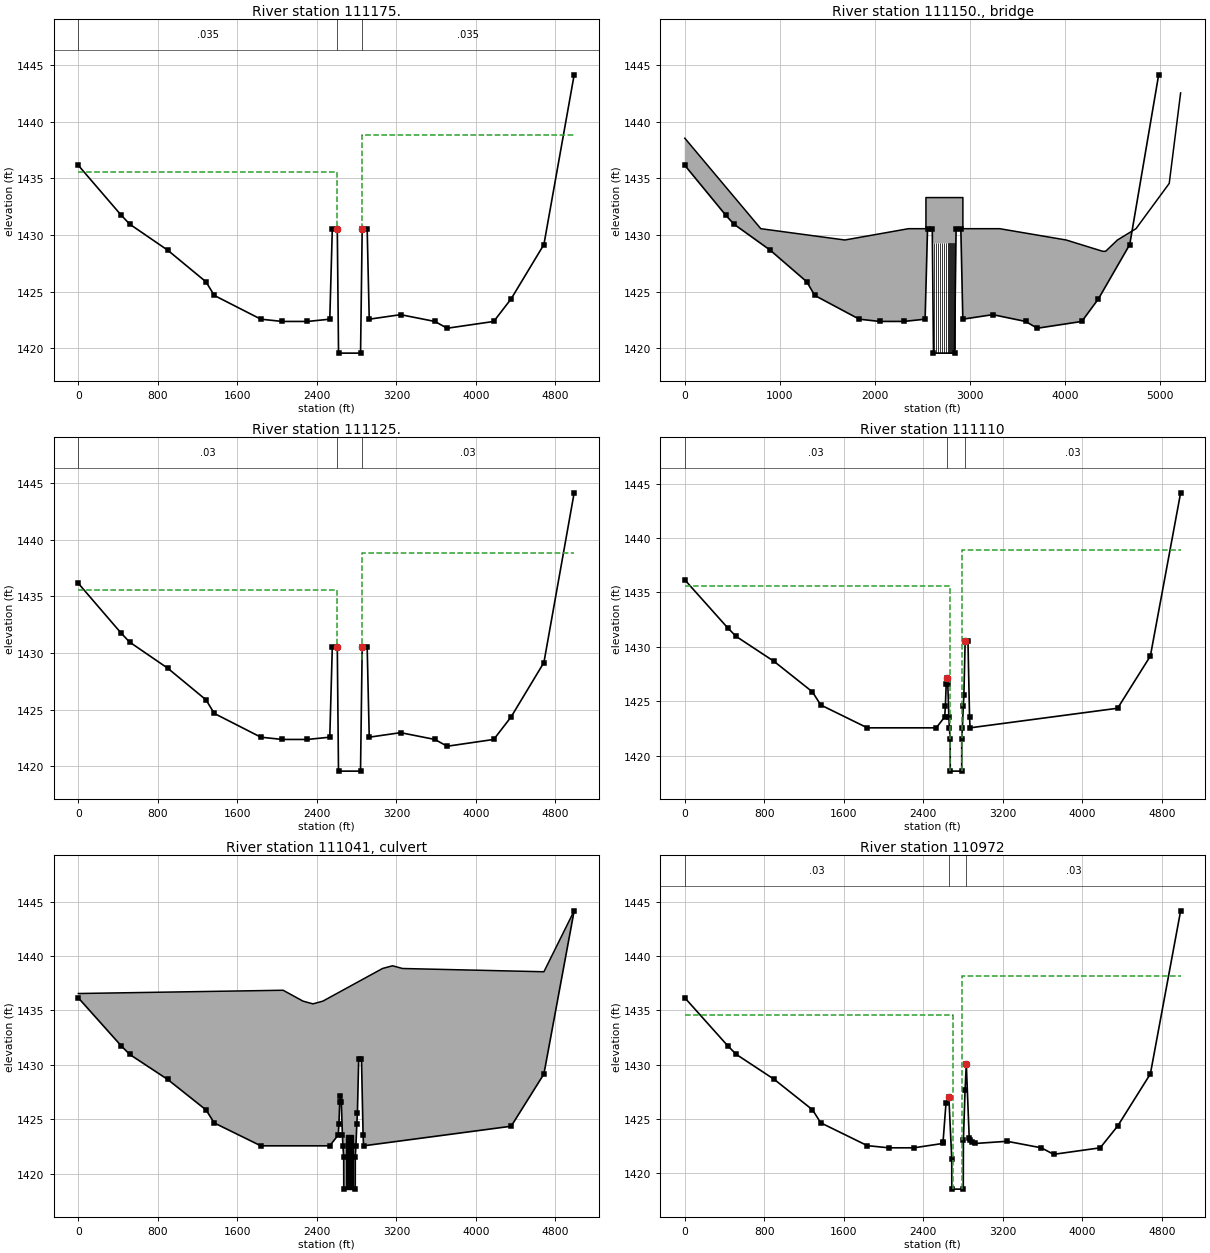
Type RM Length L Ch R = 1 ,111175. ,50,50,50
BEGIN DESCRIPTION:
This is xsec 7000 (RCFCD data  from xsec 200100 to 207000) modified to U/S face of Ramona Expressway Bridge and adjusted to fit bridge approach.  The updated data comes from RCFC&WCD San Jancinto River map, portion of section T4SR2W,Sheet 5 of 13.  Greater topo detail was avialable from this map for the approach roads to the bridge from both directions. GR data was taken on the center line of the road from the edge of bridge crossing to the outer banks.
END DESCRIPTION:
#Sta/Elev= 24
       0 1436.16   430.4 1431.76   517.1 1430.96   899.1 1428.66  1284.7 1425.86
  1367.8 1424.66  1836.4 1422.56  2052.3 1422.36  2305.1 1422.36    2530 1422.56
  2555.5 1430.56  2605.5 1430.56  2618.1 1419.56  2839.7 1419.56  2856.1 1430.56
  2906.1 1430.56    2927 1422.56  3242.4 1422.96  3587.4 1422.36  3711.1 1421.76
  4179.7 1422.36    4355 1424.36  4684.4 1429.16  4988.8 1444.16
#Mann= 3 , 0 , 0
       0    .035       0  2605.5    .035       0  2856.1    .035       0
#XS Ineff= 2 , 0
       0  2605.5 1435.61  2856.1       0 1438.86
Permanent Ineff=
       F       F
Bank Sta=2605.5,2856.1
XS Rating Curve= 0 ,0
Exp/Cntr=0.3,0.1

Type RM Length L Ch R = 3 ,111150. ,,,
BEGIN DESCRIPTION:
Existing Ramona Expressway Bridge
Bridge piers were modeled twice the size to accomodate the piers that are behind the front piers.  This was done to represent the 10 degree skew.  The levees were modeled to what the plans and field notes show.  The overlaying area were taken from the topo maps.
END DESCRIPTION:
Bridge Culvert-0,0,-1,-1, 0
Deck Dist Width WeirC Skew NumUp NumDn MinLoCord MaxHiCord MaxSubmerge Is_Ogee
10,30,2.6,0, 41, 41, , , 0.95, 0, 1,1,,
       0     400     800    1685    2355  2538.7  2538.7    2600    2600 2605.25
 2605.25  2605.5  2605.5    2705    2770  2782.4    2850  2852.3  2852.3  2856.7
 2861.25 2861.25  2862.6  2862.6  2927.7  2927.7    2940    2970    3000    3015
    3315    4015    4400    4405    4425    4430    4555    4750    5100    5160
    5220
 1438.56 1434.56 1430.56 1429.56 1430.56 1430.56 1433.31 1433.31 1433.31 1433.31
 1433.31 1433.31 1433.31 1433.31 1433.31 1433.31 1433.31 1433.31 1433.31 1433.31
 1433.31 1433.31 1433.31 1433.31 1433.31 1430.56 1430.56 1430.56 1430.56 1430.56
 1430.56 1429.56 1428.56 1428.56 1428.56 1428.56 1429.56 1430.56 1434.56 1438.56
 1442.56
                                                                                
                 1429.26 1429.26 1429.26 1429.26 1429.26 1429.26
                                                                                
                                                                                
        
       0     400     800    1685    2355  2538.7  2538.7    2600    2600 2605.25
 2605.25  2605.5  2605.5    2705    2770  2782.4    2850  2852.3  2852.3  2856.7
 2861.25 2861.25  2862.6  2862.6  2927.7  2927.7    2940    2970    3000    3015
    3315    4015    4400    4405    4425    4430    4555    4750    5100    5160
    5220
 1438.56 1434.56 1430.56 1429.56 1430.56 1430.56 1433.31 1433.31 1433.31 1433.31
 1433.31 1433.31 1433.31 1433.31 1433.31 1433.31 1433.31 1433.31 1433.31 1433.31
 1433.31 1433.31 1433.31 1433.31 1433.31 1430.56 1430.56 1430.56 1430.56 1430.56
 1430.56 1429.56 1428.56 1428.56 1428.56 1428.56 1429.56 1430.56 1434.56 1438.56
 1442.56
                                                                                
                 1429.26 1429.26 1429.26 1429.26 1429.26 1429.26
                                                                                
                                                                                
        
Pier Skew, UpSta & Num, DnSta & Num=  ,2623.65, 2 ,2623.65, 2 , 0 , 0 , 0 ,,
     2.6     2.6
 1387.56 1430.56
     2.6     2.6
 1387.56 1430.56
Pier Skew, UpSta & Num, DnSta & Num=  ,2645.31, 2 ,2645.31, 2 , 0 , 0 , 0 ,,
     2.6     2.6
 1387.56 1430.56
     2.6     2.6
 1387.56 1430.56
Pier Skew, UpSta & Num, DnSta & Num=  ,2666.97, 2 ,2666.97, 2 , 0 , 0 , 0 ,,
     2.6     2.6
 1387.56 1430.56
     2.6     2.6
 1387.56 1430.56
Pier Skew, UpSta & Num, DnSta & Num=  ,2688.63, 2 ,2688.63, 2 , 0 , 0 , 0 ,,
     2.6     2.6
 1387.56 1430.56
     2.6     2.6
 1387.56 1430.56
Pier Skew, UpSta & Num, DnSta & Num=  ,2710.29, 2 ,2710.29, 2 , 0 , 0 , 0 ,,
     2.6     2.6
 1387.56 1430.56
     2.6     2.6
 1387.56 1430.56
Pier Skew, UpSta & Num, DnSta & Num=  ,2731.95, 2 ,2731.95, 2 , 0 , 0 , 0 ,,
     2.6     2.6
 1387.56 1430.56
     2.6     2.6
 1387.56 1430.56
Pier Skew, UpSta & Num, DnSta & Num=  ,2753.61, 2 ,2753.61, 2 , 0 , 0 , 0 ,,
     2.6     2.6
 1387.56 1430.56
     2.6     2.6
 1387.56 1430.56
Pier Skew, UpSta & Num, DnSta & Num=  ,2775.27, 2 ,2775.27, 2 , 0 , 0 , 0 ,,
     2.6     2.6
 1387.56 1430.56
     2.6     2.6
 1387.56 1430.56
Pier Skew, UpSta & Num, DnSta & Num=  ,2796.93, 2 ,2796.93, 2 , 0 , 0 , 0 ,,
     2.6     2.6
 1387.56 1430.56
     2.6     2.6
 1387.56 1430.56
Pier Skew, UpSta & Num, DnSta & Num=  ,2818.59, 2 ,2818.59, 2 , 0 , 0 , 0 ,,
     2.6     2.6
 1387.56 1430.56
     2.6     2.6
 1387.56 1430.56
Pier Skew, UpSta & Num, DnSta & Num=  ,2840.25, 2 ,2840.25, 2 , 0 , 0 , 0 ,,
     2.6     2.6
 1387.56 1430.56
     2.6     2.6
 1387.56 1430.56
BR Coef=-1 , 1 , 0 ,0.9, 0 ,,,0.8,-1,1.2,0,
WSPro=,,,, 1 ,,,, 0 ,,,, 0 ,,,,-1 ,-1 ,-1 , 0 , 0 , 0 , 0 , 0
BC Design=,, 0 ,, 0 ,,,,,,
BC HTab HWMax=1444.16
BC Use User HTab Curves=0
BC User HTab FreeFlow(D)= 0

Type RM Length L Ch R = 1 ,111125. ,15,15,15
BEGIN DESCRIPTION:
This is a copy of xsec 6990 (RCFCD data  from xsec 200100 to 207000) copied to D/S face of Ramona Expressway Bridge
(this section was copied from 206800)
END DESCRIPTION:
#Sta/Elev= 24
       0 1436.16   430.4 1431.76   517.1 1430.96   899.1 1428.66  1284.7 1425.86
  1367.8 1424.66  1836.4 1422.56  2052.3 1422.36  2305.1 1422.36    2530 1422.56
  2555.5 1430.56  2605.5 1430.56  2617.7 1419.56  2839.3 1419.56  2856.1 1430.56
  2906.1 1430.56    2927 1422.56  3242.4 1422.96  3587.4 1422.36  3711.1 1421.76
  4179.7 1422.36    4355 1424.36  4684.4 1429.16  4988.8 1444.16
#Mann= 3 , 0 , 0
       0     .03       0  2605.5    .035       0  2856.1     .03       0
#XS Ineff= 2 , 0
       0 2598.43 1435.61 2854.33       0 1438.86
Permanent Ineff=
       F       F
Bank Sta=2605.5,2856.1
XS Rating Curve= 0 ,0
Exp/Cntr=0.3,0.1

Type RM Length L Ch R = 1 ,111110  ,138,138,138
BEGIN DESCRIPTION:
20 feet u/s of culvert face
END DESCRIPTION:
#Sta/Elev= 29
       0 1436.16   430.4 1431.76   517.1 1430.96   899.1 1428.66  1284.7 1425.86
  1367.8 1424.66  1836.4 1422.56    2530 1422.56    2615 1423.56    2622 1424.56
    2630 1426.56    2637 1427.16    2646 1426.56    2657 1423.56    2662 1422.56
    2670 1421.56  2670.8 1418.58  2786.2 1418.58  2786.5 1421.56    2793 1422.56
    2802 1424.56    2808 1425.56    2821 1430.56    2849 1430.56    2865 1423.56
    2870 1422.56    4355 1424.36  4684.4 1429.16  4988.8 1444.16
#Mann= 3 , 0 , 0
       0     .03       0    2637    .035       0    2821     .03       0
#XS Ineff= 2 , 0
       0  2670.8 1435.61  2786.2       0 1438.86
Permanent Ineff=
       F       F
Bank Sta=2637,2821
XS Rating Curve= 0 ,0
Exp/Cntr=0.3,0.1

Type RM Length L Ch R = 2 ,111041  ,,,
BEGIN DESCRIPTION:
Proposed 7 - 10 X 5 culverts for eastbound Ramona
END DESCRIPTION:
Bridge Culvert--1,0,-1,-1, 0
Deck Dist Width WeirC Skew NumUp NumDn MinLoCord MaxHiCord MaxSubmerge Is_Ogee
47,42,3,0, 10, 10, , , 0.95, 0, 4,4,,
       0  2060.5  2260.5  2360.5  2460.5  3060.5  3161.5  3261.5  4684.4  4988.8
 1436.56 1436.86 1435.86 1435.61 1435.86 1438.86 1439.11 1438.86 1438.56 1444.16
                                                                                
       0  2060.5  2260.5  2360.5  2460.5  3060.5  3161.5  3261.5  4684.4  4988.8
 1436.56 1436.86 1435.86 1435.61 1435.86 1438.86 1439.11 1438.86 1438.56 1444.16
                                                                                
Multiple Barrel Culv=2,5,10,97.73,0.011,0.5,1,8,1,1418.58,1418.56, 7,Culvert #1  , 0 ,20
 2696.49 2712.09 2707.16 2722.76 2717.83 2733.43  2728.5  2744.1 2739.17 2754.77
 2749.84 2765.44 2760.51 2776.11
Culvert Bottom n=0.011
BC Design=,, 0 ,, 0 ,,,,,,
BC HTab HWMax=1444.16
BC Use User HTab Curves=0
BC User HTab FreeFlow(D)= 0

Type RM Length L Ch R = 1 ,110972  ,62,62,62
BEGIN DESCRIPTION:
20.27 feet d/s of culvert face
END DESCRIPTION:
#Sta/Elev= 30
       0 1436.16   430.4 1431.76   517.1 1430.96   899.1 1428.66  1284.7 1425.86
  1367.8 1424.66  1836.4 1422.56  2052.3 1422.36  2305.1 1422.36  2595.2 1422.76
    2598 1422.86    2628 1426.46  2656.6 1427.06  2685.9 1421.36  2686.4 1418.56
  2801.8 1418.56  2803.1 1423.06  2819.9 1427.66  2832.4 1430.06  2861.7 1423.26
  2867.9 1423.06    2891 1422.86  2923.2 1422.76  3242.4 1422.96  3587.4 1422.36
  3711.1 1421.76  4179.7 1422.36    4355 1424.36  4684.4 1429.16  4988.8 1444.16
#Mann= 3 , 0 , 0
       0     .03       0  2656.6    .035       0  2832.4     .03       0
#XS Ineff= 2 , 0
       0  2701.6 1434.61  2786.6       0 1438.16
Permanent Ineff=
       F       F
Bank Sta=2656.6,2832.4
XS Rating Curve= 0 ,0
Exp/Cntr=0.3,0.1

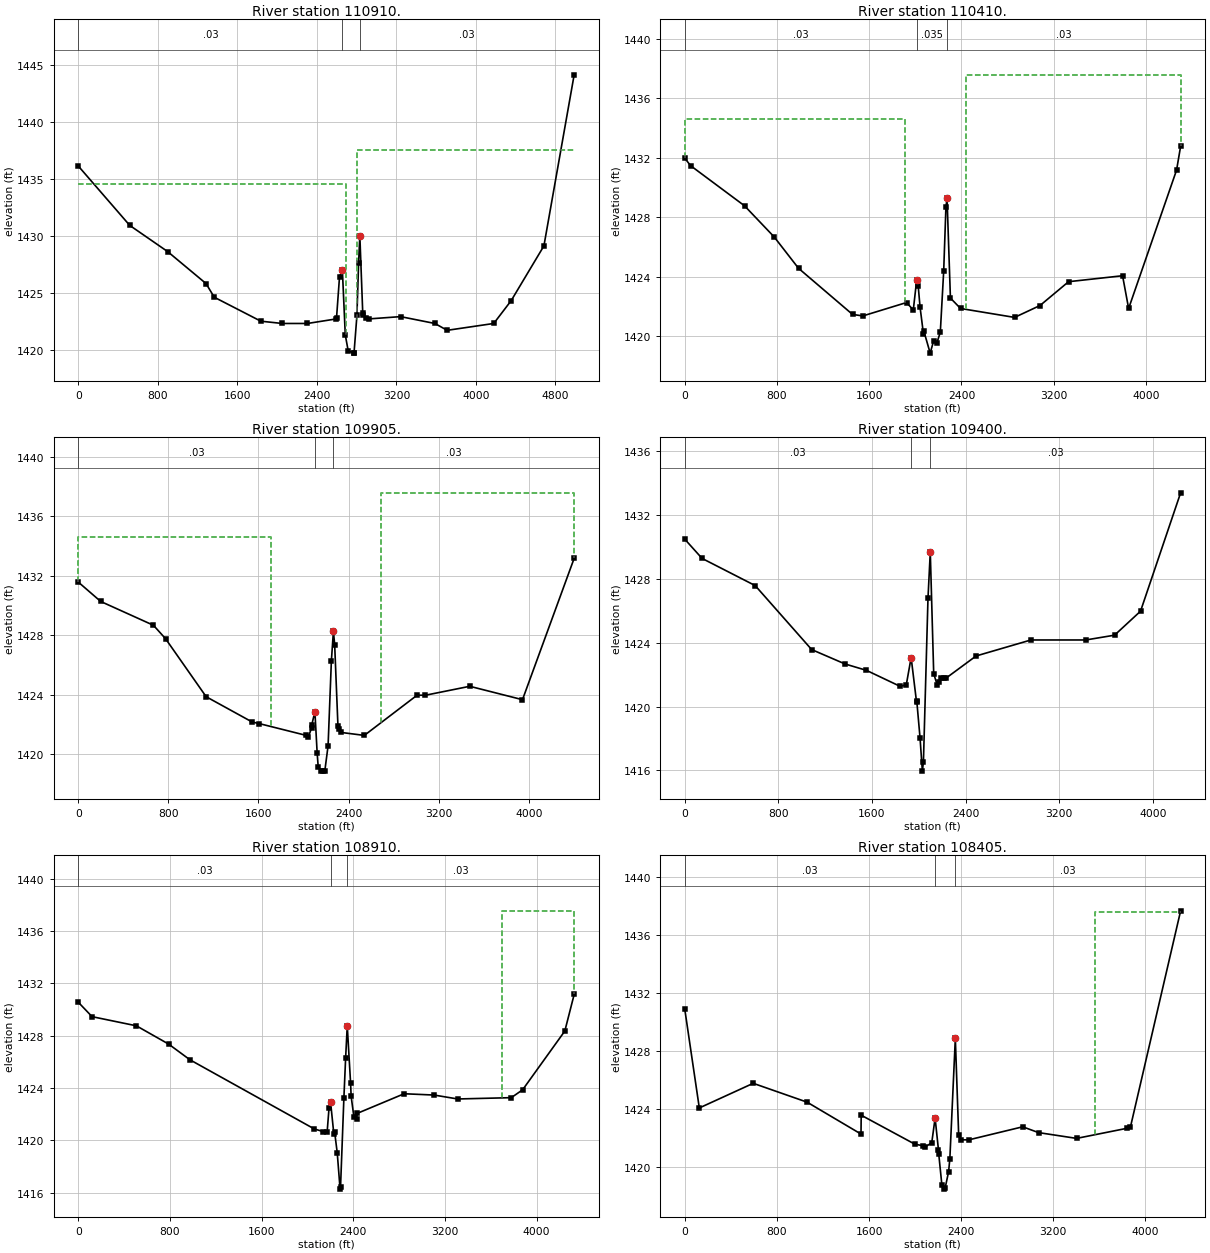
Type RM Length L Ch R = 1 ,110910. ,500,500,500
BEGIN DESCRIPTION:
6800
END DESCRIPTION:
#Sta/Elev= 30
       0 1436.16   517.1 1430.96   899.1 1428.66  1284.7 1425.86  1367.8 1424.66
  1836.4 1422.56  2052.3 1422.36  2305.1 1422.36  2595.2 1422.76    2598 1422.86
    2628 1426.46  2656.6 1427.06  2685.9 1421.36  2715.2 1419.96  2771.9 1419.76
  2773.8 1419.76  2803.1 1423.06  2819.9 1427.66  2832.4 1430.06  2861.7 1423.26
  2867.9 1423.06    2891 1422.86  2923.2 1422.76  3242.4 1422.96  3587.4 1422.36
  3711.1 1421.76  4179.7 1422.36    4355 1424.36  4684.4 1429.16  4988.8 1444.16
#Mann= 3 , 0 , 0
       0     .03       0  2656.6    .035       0  2832.4     .03       0
#XS Ineff= 2 , 0
       0  2689.5 1434.56  2799.5       0 1437.56
Permanent Ineff=
       F       F
Bank Sta=2656.6,2832.4
XS Rating Curve= 0 ,0
Exp/Cntr=0.3,0.1

Type RM Length L Ch R = 1 ,110410. ,505,505,505
BEGIN DESCRIPTION:
6700
END DESCRIPTION:
#Sta/Elev= 30
       0 1431.96    49.6 1431.46     518 1428.76   776.1 1426.66   986.5 1424.56
    1455 1421.46  1544.5 1421.36  1923.4 1422.26    1982 1421.76  2011.3 1423.76
  2024.8 1423.36  2040.6 1421.96  2069.9 1420.16  2072.9 1420.36  2128.4 1418.86
  2157.7 1419.66    2187 1419.56  2216.3 1420.26  2245.6 1424.36    2265 1428.66
  2274.8 1429.26  2304.1 1422.56  2391.9 1421.86  2860.4 1421.26  3081.4 1422.06
  3328.9 1423.66  3797.3 1424.06  3849.9 1421.86  4265.8 1431.16  4300.9 1432.76
#Mann= 3 , 0 , 0
       0     .03       0  2011.3    .035       0  2274.8     .03       0
#XS Ineff= 2 , 0
       0    1910 1434.56    2440       0 1437.56
Permanent Ineff=
       F       F
Bank Sta=2011.3,2274.8
XS Rating Curve= 0 ,0
Exp/Cntr=0.3,0.1

Type RM Length L Ch R = 1 ,109905. ,505,505,505
BEGIN DESCRIPTION:
6600
END DESCRIPTION:
#Sta/Elev= 30
       0 1431.56   198.8 1430.26     667 1428.66   774.4 1427.76  1135.2 1423.86
  1543.9 1422.16  1603.4 1422.06  2024.2 1421.26  2042.4 1421.16  2071.7 1421.76
    2073 1421.96  2100.9 1422.86  2121.1 1420.06  2130.2 1419.16  2159.4 1418.86
  2169.2 1418.86  2188.7 1418.86    2218 1420.56  2247.2 1426.26  2265.4 1428.26
  2276.5 1427.36  2305.8 1421.86  2313.5 1421.66  2333.3 1421.46  2539.9 1421.26
  3008.1 1423.96    3083 1423.96  3476.3 1424.56  3944.5 1423.66  4403.4 1433.16
#Mann= 3 , 0 , 0
       0     .03       0  2100.9    .035       0  2265.4     .03       0
#XS Ineff= 2 , 0
       0    1710 1434.56    2690       0 1437.56
Permanent Ineff=
       F       F
Bank Sta=2100.9,2265.4
XS Rating Curve= 0 ,0
Exp/Cntr=0.3,0.1

Type RM Length L Ch R = 1 ,109400. ,490,490,490
BEGIN DESCRIPTION:
6500
END DESCRIPTION:
#Sta/Elev= 28
       0 1430.46   147.4 1429.26   601.8 1427.56  1084.5 1423.56  1369.8 1422.66
  1553.1 1422.26    1841 1421.26  1893.5 1421.36  1934.9 1423.06  1981.4 1420.26
  1982.9 1420.36  2010.7 1418.06  2030.9 1415.96    2040 1416.56  2078.9 1426.76
  2098.5 1429.66  2127.8 1422.06  2157.1 1421.36  2174.9 1421.56  2186.4 1421.76
  2215.7 1421.76  2230.6 1421.76  2490.2 1423.16  2958.8 1424.16  3427.4 1424.16
  3673.9 1424.46  3895.9 1425.96  4238.6 1433.36
#Mann= 3 , 0 , 0
       0     .03       0  1934.9    .035       0  2098.5     .03       0
Bank Sta=1934.9,2098.5
XS Rating Curve= 0 ,0
Exp/Cntr=0.3,0.1

Type RM Length L Ch R = 1 ,108910. ,505,505,505
BEGIN DESCRIPTION:
6400
WEST:  Measured from zero back 120 feet to obtain elevation 1428.  Then added 120 constant to all stationing in order to remove of the negative 120 feet measurement. (RCFCD photo maps)
END DESCRIPTION:
#Sta/Elev= 30
       0 1430.56     120 1429.46   506.7 1428.76   788.4 1427.36   974.3 1426.16
  2061.3 1420.86  2140.3 1420.66  2172.4 1420.66  2188.6 1422.46  2201.6 1422.96
  2230.9 1420.46  2236.9 1420.66  2260.1 1419.06  2285.2 1416.26  2289.3 1416.46
  2318.5 1423.26  2333.4 1426.26  2347.7 1428.76    2377 1424.36  2381.7 1423.36
  2406.2 1421.76    2430 1421.66  2435.4 1422.06  2844.5 1423.56    3106 1423.46
  3312.1 1423.16  3779.6 1423.26  3878.5 1423.86  4247.2 1428.36  4328.7 1431.16
#Mann= 3 , 0 , 0
       0     .03       0  2201.6    .035       0  2347.7     .03       0
#XS Ineff= 2 , 0
       0                    3701       0 1437.56
Permanent Ineff=
       F       F
Bank Sta=2201.6,2347.7
XS Rating Curve= 0 ,0
Exp/Cntr=0.3,0.1

Type RM Length L Ch R = 1 ,108405. ,510,510,510
BEGIN DESCRIPTION:
6300
END DESCRIPTION:
#Sta/Elev= 28
       0 1430.86     126 1424.06   594.1 1425.76  1062.2 1424.46  1530.3 1422.26
    1532 1423.56  1998.4 1421.56  2064.9 1421.46  2086.2 1421.36  2144.7 1421.66
  2173.9 1423.36  2203.2 1421.16  2205.8 1420.86  2232.5 1418.76  2253.9 1418.46
  2261.7 1418.56    2291 1419.66    2302 1420.56  2349.5 1428.86  2378.7 1422.16
  2398.3 1421.86  2466.5 1421.86  2934.6 1422.76  3072.1 1422.36  3402.7 1421.96
  3842.2 1422.66  3870.8 1422.76  4306.2 1437.66
#Mann= 3 , 0 , 0
       0     .03       0  2173.9    .035       0  2349.5     .03       0
#XS Ineff= 2 , 0
       0                    3560       0 1437.56
Permanent Ineff=
       F       F
Bank Sta=2173.9,2349.5
XS Rating Curve= 0 ,0
Exp/Cntr=0.3,0.1

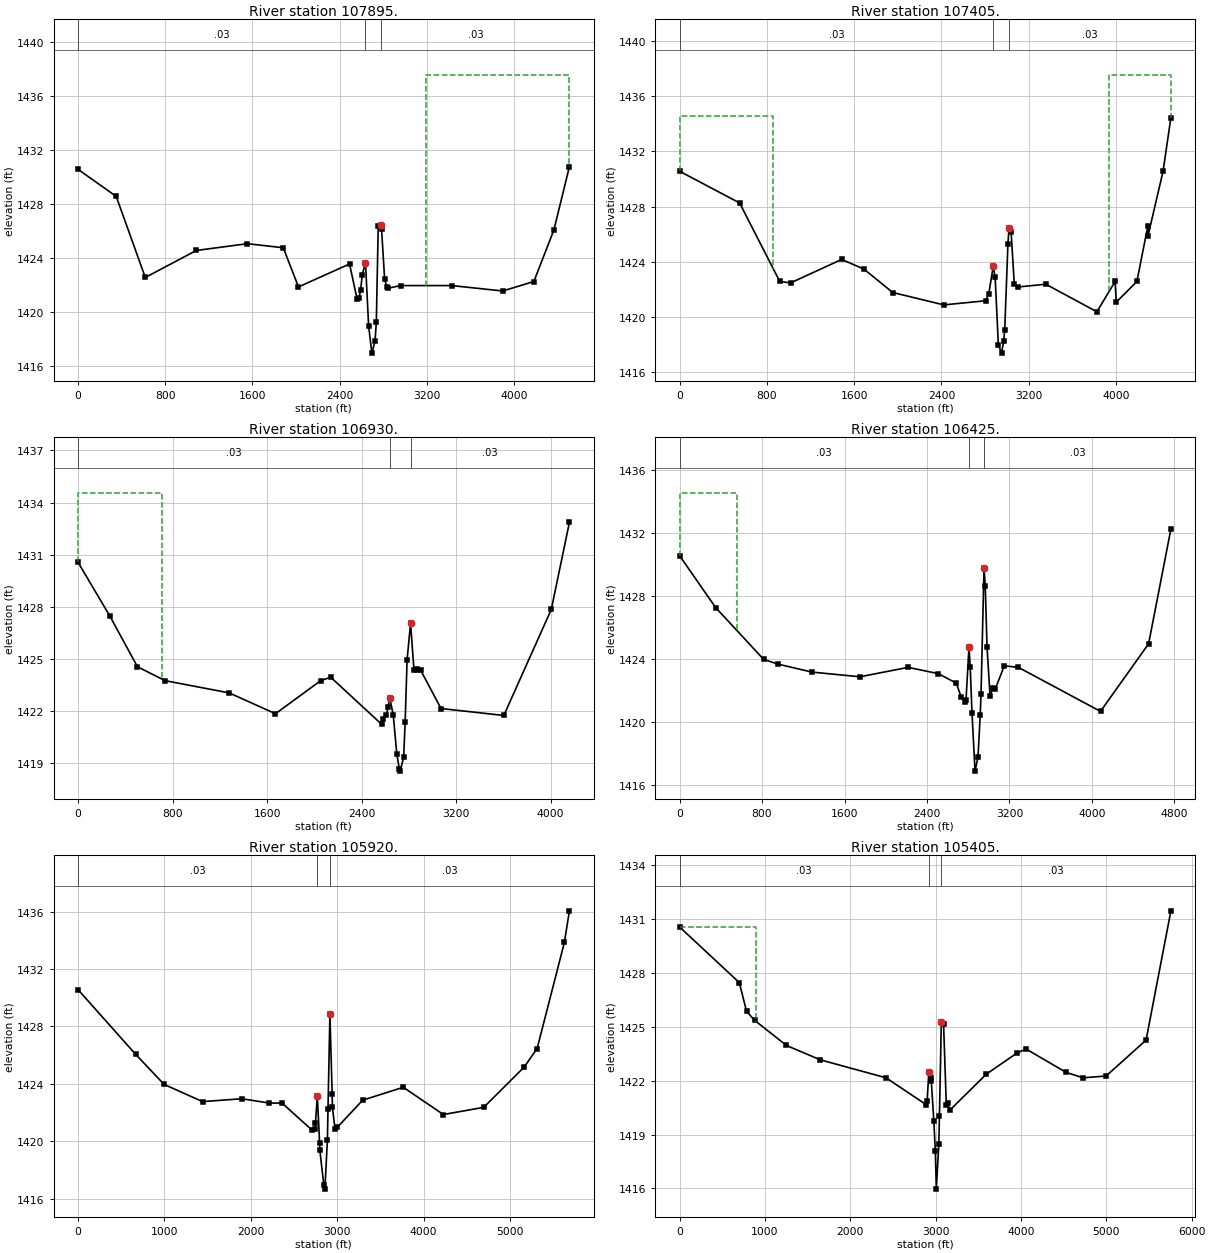
Type RM Length L Ch R = 1 ,107895. ,490,490,490
BEGIN DESCRIPTION:
6200
WEST:  Measured back from zero 350 feet to obtain 1428 ft. elevation.  Added 350 constant to all stationing in order to remove -350 feet measurement. (RCFCD photo maps)
END DESCRIPTION:
#Sta/Elev= 29
       0 1430.56     350 1428.56   616.8 1422.56  1085.6 1424.56  1554.4 1425.06
  1883.7 1424.76  2023.3 1421.86  2492.1 1423.56  2561.3 1420.96  2579.6 1421.06
  2594.2 1421.66  2608.9 1422.76  2638.2 1423.66  2667.5 1418.96  2696.8 1416.96
  2726.1 1417.86    2738 1419.26  2755.4 1426.36  2784.7 1426.46  2785.9 1426.16
    2814 1422.46  2833.8 1421.86  2843.3 1421.76  2960.9 1421.96  3429.8 1421.96
    3898 1421.56  4184.1 1422.26  4367.5 1426.06  4510.7 1430.76
#Mann= 3 , 0 , 0
       0     .03       0  2638.2    .035       0  2784.7     .03       0
#XS Ineff= 2 , 0
       0                    3190       0 1437.56
Permanent Ineff=
       F       F
Bank Sta=2638.2,2784.7
XS Rating Curve= 0 ,0
Exp/Cntr=0.3,0.1

Type RM Length L Ch R = 1 ,107405. ,475,475,475
BEGIN DESCRIPTION:
6100
WEST: Measured back from zero 550 feet to obtain 1428 ft. elevation.  Added 550 feet constant to start at 0 . (RCFCD photo maps)
END DESCRIPTION:
#Sta/Elev= 30
       0 1430.56     550 1428.26   918.3 1422.56  1017.9 1422.46  1485.7 1424.16
  1689.4 1423.46  1953.6 1421.76  2421.5 1420.86  2804.7 1421.16  2833.9 1421.66
  2874.6 1423.66  2892.4 1422.86  2921.6 1417.96  2950.9 1417.36    2971 1418.26
  2980.1 1419.06  3009.4 1425.26  3019.2 1426.46  3038.6 1426.16  3067.8 1422.36
  3099.2 1422.16  3357.2 1422.36    3825 1420.36  3991.4 1422.56  4002.8 1421.06
  4191.4 1422.56  4291.4 1426.56  4292.9 1425.86  4431.4 1430.56  4503.3 1434.46
#Mann= 3 , 0 , 0
       0     .03       0  2874.6    .035       0  3019.2     .03       0
#XS Ineff= 2 , 0
       0     860 1434.56    3940       0 1437.56
Permanent Ineff=
       F       F
Bank Sta=2874.6,3019.2
XS Rating Curve= 0 ,0
Exp/Cntr=0.3,0.1

Type RM Length L Ch R = 1 ,106930. ,505,505,505
BEGIN DESCRIPTION:
6000
WEST:  Measured back from zero 350 feet to obtain 1428 ft elevation.  Added 270 feet to remove negative number. (RCFCD photo maps)
END DESCRIPTION:
#Sta/Elev= 29
       0 1430.56     270 1427.46   502.4 1424.56     737 1423.76  1277.7 1423.06
  1670.8 1421.86    2053 1423.76  2137.8 1423.96  2568.4 1421.26  2580.5 1421.56
  2609.7 1421.76  2622.9 1422.26  2638.9 1422.76  2668.1 1421.76  2697.3 1419.56
  2719.8 1418.66  2726.5 1418.56  2755.7 1419.36  2768.3 1421.36  2784.8 1424.96
    2814 1427.06  2843.2 1424.36  2865.2 1424.36  2872.4 1424.46  2899.7 1424.36
  3071.7 1422.16  3603.5 1421.76  4005.6 1427.86  4158.8 1432.86
#Mann= 3 , 0 , 0
       0     .03       0  2638.9    .035       0    2814     .03       0
#XS Ineff= 2 , 0
       0     710 1434.56               0
Permanent Ineff=
       F       F
Bank Sta=2638.9,2814
XS Rating Curve= 0 ,0
Exp/Cntr=0.3,0.1

Type RM Length L Ch R = 1 ,106425. ,505,505,505
BEGIN DESCRIPTION:
5900
WEST:  Measured back from zero 350 feet to obtain 1428 ft elevation.  Added 350 feet constant to all stations to correct zero. (RCFCD photo maps)
END DESCRIPTION:
#Sta/Elev= 30
       0 1430.56     350 1427.26   816.7 1423.96   958.1 1423.66  1283.5 1423.16
  1750.2 1422.86  2216.9 1423.46  2510.7 1423.06  2683.7 1422.46  2733.5 1421.56
  2771.5 1421.26  2778.7 1421.36  2807.9 1424.76    2820 1423.46  2837.1 1420.56
  2866.2 1416.86  2895.4 1417.76  2917.1 1420.46  2924.6 1421.76  2953.7 1429.76
  2965.6 1428.66  2982.9 1424.76  3012.1 1421.66  3041.2 1422.16  3061.8 1422.06
  3150.4 1423.56    3287 1423.46  4083.9 1420.66  4550.6 1424.96    4767 1432.26
#Mann= 3 , 0 , 0
       0     .03       0  2807.9    .035       0  2953.7     .03       0
#XS Ineff= 2 , 0
       0     560 1434.56               0
Permanent Ineff=
       F       F
Bank Sta=2807.9,2953.7
XS Rating Curve= 0 ,0
Exp/Cntr=0.3,0.1

Type RM Length L Ch R = 1 ,105920. ,515,515,515
BEGIN DESCRIPTION:
5800
WEST:  Measured 600 feet back from zero to obtain 1428 ft elevation.  Added 600 constant to all stations (RCFCD photo maps)
END DESCRIPTION:
#Sta/Elev= 30
       0 1430.56   665.5 1426.06   995.7 1423.96  1440.3 1422.76  1893.8 1422.96
  2215.2 1422.66  2360.8 1422.66  2711.2 1420.76  2740.3 1420.86  2747.9 1421.26
  2769.5 1423.16  2796.3 1419.86  2798.7 1419.36  2844.7 1416.96  2857.1 1416.66
  2886.3 1420.06  2893.2 1422.26  2915.5 1428.86  2941.6 1423.26  2944.7 1422.36
  2973.9 1420.86  2999.3 1420.96  3294.9 1422.86  3764.8 1423.76    4229 1421.86
  4696.1 1422.36  5163.1 1425.16  5314.5 1426.46  5630.2 1433.86  5688.3 1436.06
#Mann= 3 , 0 , 0
       0     .03       0  2769.5    .035       0  2915.5     .03       0
Bank Sta=2769.5,2915.5
XS Rating Curve= 0 ,0
Exp/Cntr=0.3,0.1

Type RM Length L Ch R = 1 ,105405. ,495,495,495
BEGIN DESCRIPTION:
5700
WEST:  Measured back from zero 700 feet to obtain 1428 elevation.  Added 700 constant to all stations (RCFCD photo maps)
END DESCRIPTION:
#Sta/Elev= 30
       0 1430.56     700 1427.46   784.4 1425.86   879.4 1425.36  1252.5 1423.96
  1649.3 1423.16  2419.2 1422.16    2891 1420.66  2900.4 1420.86  2920.2 1422.46
  2948.5 1422.16  2949.5 1421.96  2978.8 1419.76  2996.6 1418.06    3008 1415.96
  3037.3 1418.46  3044.7 1420.06  3066.6 1425.26  3092.9 1425.16  3125.1 1420.66
    3141 1420.76  3166.6 1420.36  3593.2 1422.36    3959 1423.56  4061.4 1423.76
  4529.5 1422.46  4728.9 1422.16  4997.6 1422.26  5465.8 1424.26  5756.8 1431.46
#Mann= 3 , 0 , 0
       0     .03       0  2920.2    .035       0  3066.6     .03       0
#XS Ineff= 2 , 0
       0     900 1430.56               0
Permanent Ineff=
       F       F
Bank Sta=2920.2,3066.6
XS Rating Curve= 0 ,0
Exp/Cntr=0.3,0.1