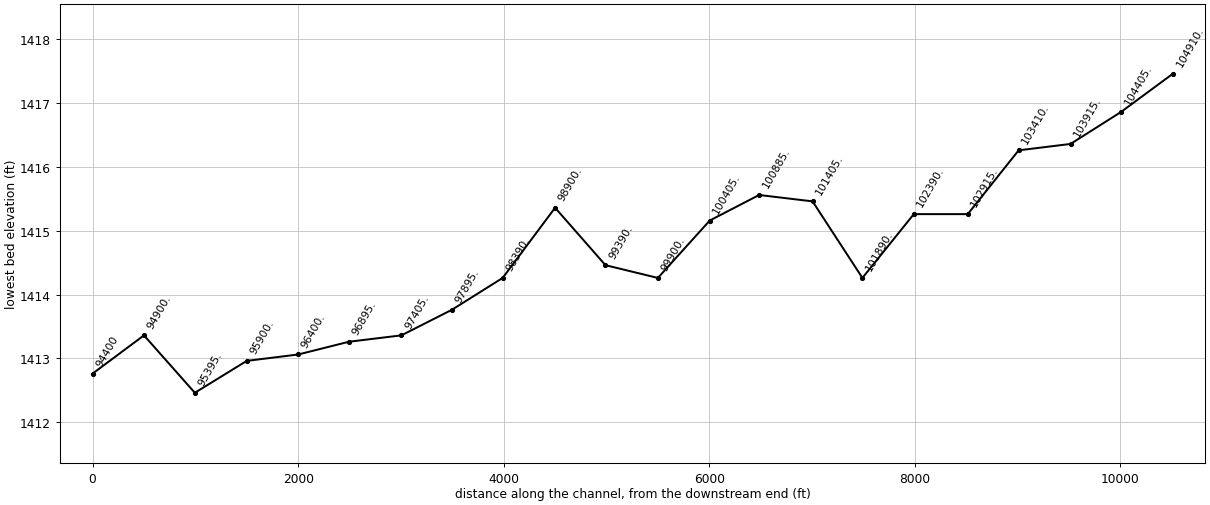
HEC-RAS study RamonaFlowControl.prj: Ramona Flow Control Rating Curve

--- RamonaFlowControl.g05 (geometry) --- (continued)

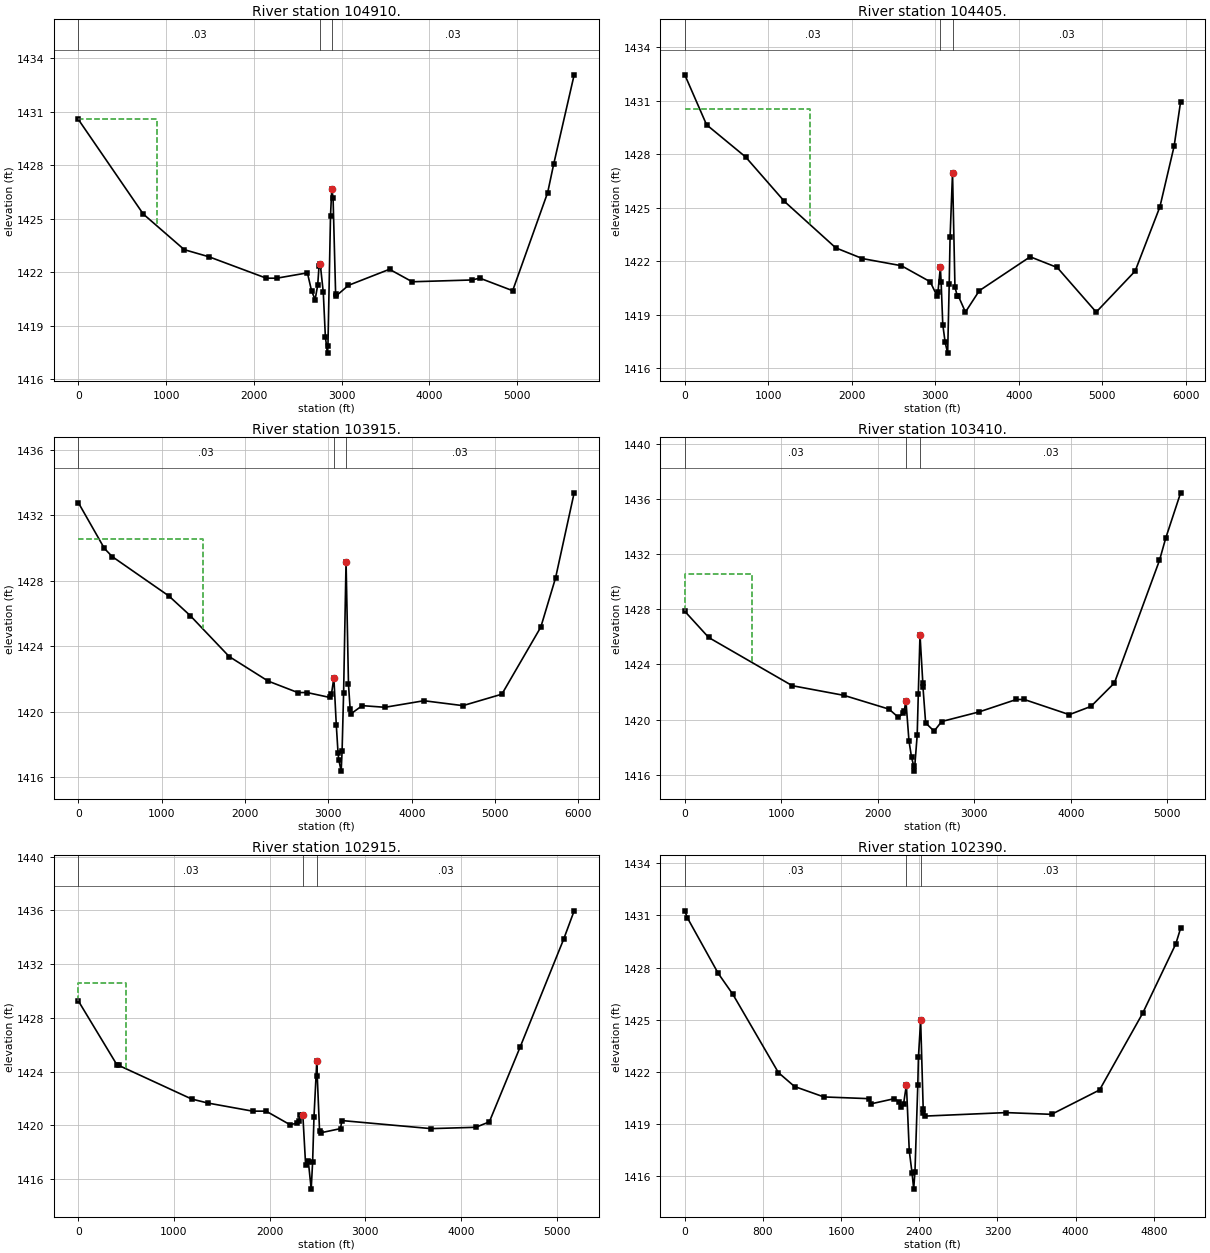
Type RM Length L Ch R = 1 ,104910. ,505,505,505
BEGIN DESCRIPTION:
5600
WEST:  Measured back from zero 470 feet to obtain 1428 ft elevation.  Added a 470 constant to all stations. (RCFCD photo maps)
END DESCRIPTION:
#Sta/Elev= 30
       0 1430.56   739.2 1425.26    1207 1423.26  1488.8 1422.86  2142.4 1421.66
  2260.5 1421.66  2610.1 1421.96    2657 1420.96  2697.8 1420.46  2727.1 1421.26
  2742.9 1422.36  2756.3 1422.46  2791.1 1420.86  2814.8 1418.36  2839.4 1417.46
    2844 1417.86  2873.3 1425.16  2887.6 1426.66  2902.5 1426.16  2931.7 1420.76
  2935.9 1420.66  3077.9 1421.26  3545.6 1422.16  3804.1 1421.46    4481 1421.56
  4575.8 1421.66  4948.8 1420.96  5347.6 1426.46  5416.5 1428.06  5649.5 1433.06
#Mann= 3 , 0 , 0
       0     .03       0  2756.3    .035       0  2887.6     .03       0
#XS Ineff= 2 , 0
       0     900 1430.56               0
Permanent Ineff=
       F       F
Bank Sta=2756.3,2887.6
XS Rating Curve= 0 ,0
Exp/Cntr=0.3,0.1

Type RM Length L Ch R = 1 ,104405. ,490,490,490
BEGIN DESCRIPTION:
5500
END DESCRIPTION:
#Sta/Elev= 30
       0 1432.46   260.9 1429.66   727.6 1427.86  1194.2 1425.36  1808.3 1422.76
  2127.6 1422.16  2594.3 1421.76  2939.8 1420.86  3021.6 1420.06  3031.8 1420.26
    3061 1421.66  3070.1 1420.86  3090.1 1418.46  3118.6 1417.46  3148.5 1416.86
  3167.2 1420.76  3177.6 1423.36  3206.8 1426.96    3236 1420.56  3264.2 1420.06
  3276.9 1420.06  3361.3 1419.16  3527.6 1420.36    4137 1422.26    4461 1421.66
  4927.7 1419.16  5394.4 1421.46  5690.8 1425.06  5861.1 1428.46    5939 1430.96
#Mann= 3 , 0 , 0
       0     .03       0    3061    .035       0  3206.8     .03       0
#XS Ineff= 2 , 0
       0    1500 1430.56               0
Permanent Ineff=
       F       F
Bank Sta=3061,3206.8
XS Rating Curve= 0 ,0
Exp/Cntr=0.3,0.1

Type RM Length L Ch R = 1 ,103915. ,505,505,505
BEGIN DESCRIPTION:
5400
END DESCRIPTION:
#Sta/Elev= 30
       0 1432.76   313.1 1429.96   407.7 1429.46  1086.3 1427.06  1342.5 1425.86
  1809.9 1423.36  2277.3 1421.86  2632.9 1421.16  2744.7 1421.16  3017.8 1420.86
  3036.9 1421.06  3066.1 1422.06  3095.3 1419.16  3116.2 1417.46  3124.5 1417.06
  3153.7 1416.36  3164.5 1417.56  3182.9 1421.16  3212.2 1429.16  3241.4 1421.66
  3261.2 1420.16  3270.6 1419.86  3406.1 1420.36  3679.5 1420.26  4146.9 1420.66
  4614.3 1420.36  5081.7 1421.06  5549.1 1425.16  5725.8 1428.16  5949.1 1433.36
#Mann= 3 , 0 , 0
       0     .03       0  3066.1    .035       0  3212.2     .03       0
#XS Ineff= 2 , 0
       0    1500 1430.56               0
Permanent Ineff=
       F       F
Bank Sta=3066.1,3212.2
XS Rating Curve= 0 ,0
Exp/Cntr=0.3,0.1

Type RM Length L Ch R = 1 ,103410. ,495,495,495
BEGIN DESCRIPTION:
5300
END DESCRIPTION:
#Sta/Elev= 30
       0 1427.86   247.6 1425.96    1114 1422.46  1649.3 1421.76  2116.5 1420.76
  2214.1 1420.16  2262.5 1420.46    2275 1420.66  2291.7 1421.36  2323.4 1418.46
  2350.1 1417.26  2371.8 1416.66  2379.3 1416.26  2408.5 1418.86  2420.1 1421.86
  2437.7 1426.16  2466.9 1422.66  2468.5 1422.36  2496.1 1419.76  2583.7 1419.16
    2662 1419.86  3050.9 1420.56    3436 1421.46  3518.2 1421.46  3985.4 1420.36
    4210 1420.96  4452.6 1422.66  4919.9 1431.56    4984 1433.16  5138.9 1436.46
#Mann= 3 , 0 , 0
       0     .03       0  2291.7    .035       0  2437.7     .03       0
#XS Ineff= 2 , 0
       0     700 1430.56               0
Permanent Ineff=
       F       F
Bank Sta=2291.7,2437.7
XS Rating Curve= 0 ,0
Exp/Cntr=0.3,0.1

Type RM Length L Ch R = 1 ,102915. ,525,525,525
BEGIN DESCRIPTION:
5200
END DESCRIPTION:
#Sta/Elev= 30
       0 1429.26   407.4 1424.46   423.3 1424.46  1185.3 1421.96  1356.1 1421.66
  1822.4 1421.06  1963.1 1421.06  2210.9 1420.06  2288.9 1420.16  2303.4 1420.36
    2318 1420.76  2347.2 1420.76  2376.3 1417.06  2400.7 1417.36  2405.5 1417.26
  2434.6 1415.26  2449.3 1417.26  2463.8 1420.66  2492.9 1424.76  2497.9 1423.66
  2522.1 1419.56  2539.9 1419.46    2741 1419.76  2755.2 1420.36    3688 1419.76
  4154.4 1419.86  4296.7 1420.26  4620.8 1425.86  5074.5 1433.86  5183.7 1435.96
#Mann= 3 , 0 , 0
       0     .03       0  2347.2    .035       0  2492.9     .03       0
#XS Ineff= 2 , 0
       0     500 1430.56               0
Permanent Ineff=
       F       F
Bank Sta=2347.2,2492.9
XS Rating Curve= 0 ,0
Exp/Cntr=0.3,0.1

Type RM Length L Ch R = 1 ,102390. ,500,500,500
BEGIN DESCRIPTION:
5100
END DESCRIPTION:
#Sta/Elev= 30
       0 1431.26    26.1 1430.86   342.5 1427.66   491.9 1426.46   957.8 1421.96
  1122.8 1421.16  1423.6 1420.56  1889.5 1420.46  1903.2 1420.16  2144.2 1420.46
  2195.9 1420.26  2209.8 1419.96  2238.9 1420.16    2268 1421.26  2297.1 1417.46
  2326.3 1416.16  2342.3 1415.26  2355.4 1416.26  2384.5 1421.26    2391 1422.86
  2413.6 1424.96  2439.8 1419.86  2442.7 1419.66    2461 1419.46    3287 1419.66
  3752.9 1419.56  4244.4 1420.96  4684.6 1425.36  5024.8 1429.36  5074.1 1430.26
#Mann= 3 , 0 , 0
       0     .03       0    2268    .035       0  2413.6     .03       0
Bank Sta=2268,2413.6
XS Rating Curve= 0 ,0
Exp/Cntr=0.3,0.1

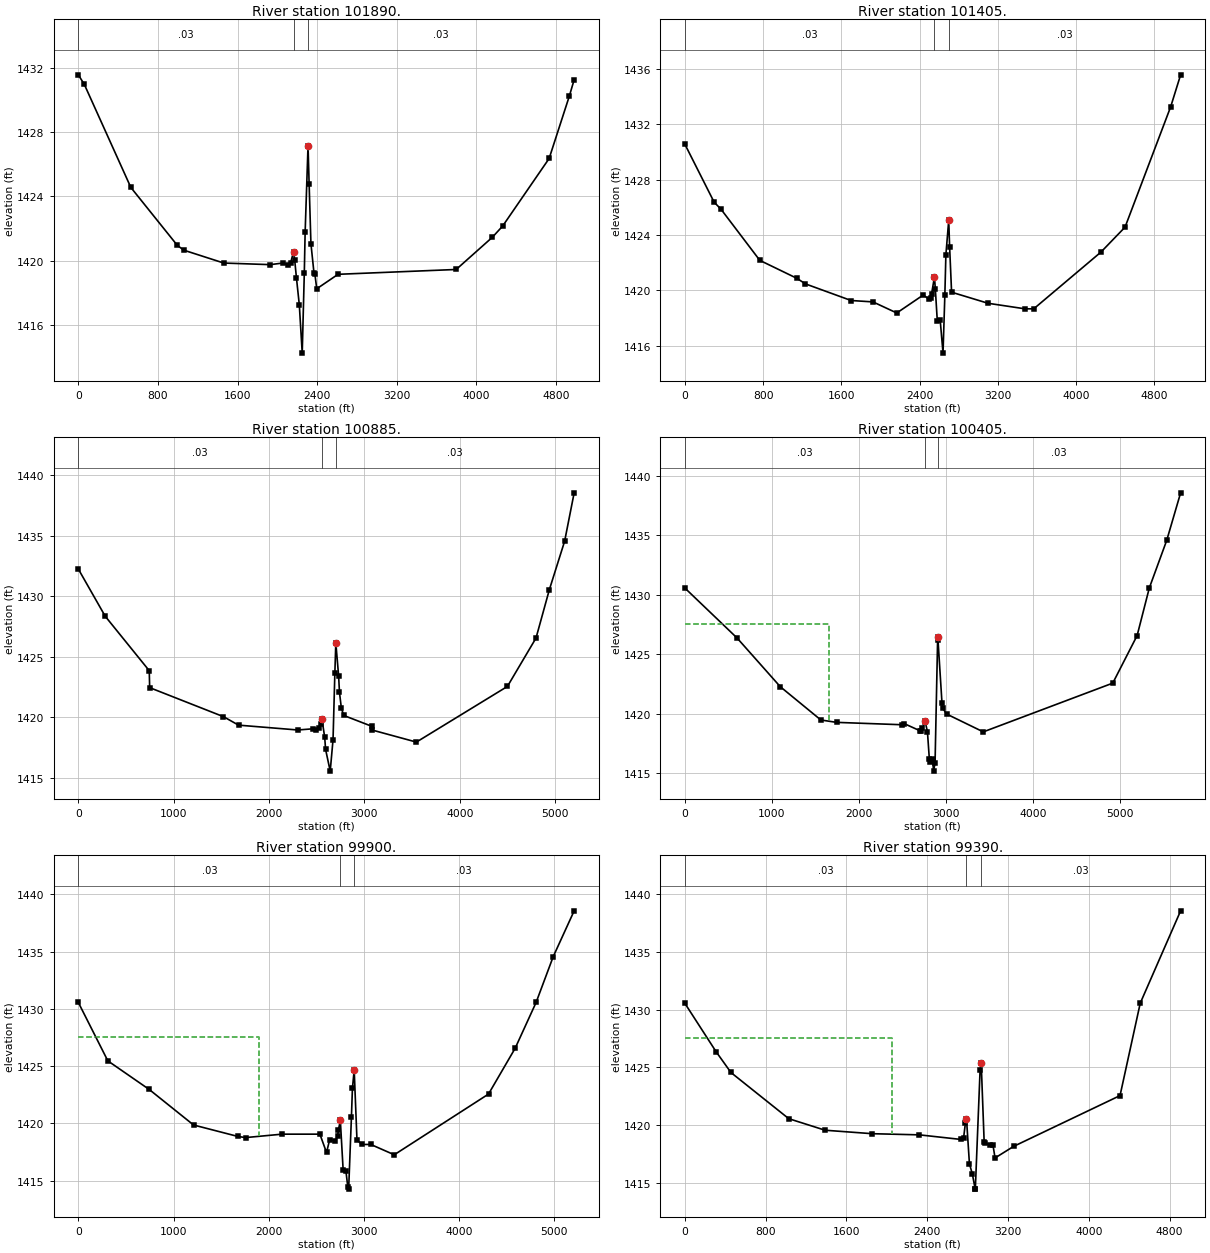
Type RM Length L Ch R = 1 ,101890. ,485,485,485
BEGIN DESCRIPTION:
5000
END DESCRIPTION:
#Sta/Elev= 30
       0 1431.56    60.5 1430.96   527.5 1424.56   994.5 1420.96  1059.7 1420.66
  1461.5 1419.86  1928.5 1419.76  2053.3 1419.86  2103.7 1419.76  2132.9 1419.86
    2162 1420.56  2173.8 1420.06  2191.2 1418.96  2220.4 1417.26  2249.6 1414.26
  2270.6 1419.26  2278.8 1421.76    2308 1427.16  2319.1 1424.76  2337.2 1421.06
  2367.5 1419.26  2377.1 1419.16  2395.6 1418.26  2609.7 1419.16  3796.6 1419.46
  4159.7 1421.46  4263.6 1422.16  4730.6 1426.36  4934.7 1430.26    4982 1431.26
#Mann= 3 , 0 , 0
       0     .03       0    2162    .035       0    2308     .03       0
Bank Sta=2162,2308
XS Rating Curve= 0 ,0
Exp/Cntr=0.3,0.1

Type RM Length L Ch R = 1 ,101405. ,520,520,520
BEGIN DESCRIPTION:
4900
WEST:  Measured back 300 feet from zero to obtain 1428 ft elevation.  Added 300 feet contstant to all stations. (RCFCD photo maps)
END DESCRIPTION:
#Sta/Elev= 30
       0 1430.56     300 1426.36   369.3 1425.86   766.6 1422.16  1146.2 1420.86
  1233.2 1420.46  1699.8 1419.26    1923 1419.16  2166.4 1418.36  2437.6 1419.66
  2493.3 1419.36  2512.1 1419.46  2522.5 1419.76  2551.7 1420.96  2560.7 1420.06
  2580.8 1417.76    2610 1417.86  2639.1 1415.46  2657.8 1419.66  2668.3 1422.56
  2697.5 1425.06  2706.3 1423.16  2726.6 1419.86  3099.6 1419.06  3476.8 1418.66
  3566.3 1418.66  4253.6 1422.76  4499.5 1424.56  4966.1 1433.26  5067.4 1435.56
#Mann= 3 , 0 , 0
       0     .03       0  2551.7    .035       0  2697.5     .03       0
Bank Sta=2551.7,2697.5
XS Rating Curve= 0 ,0
Exp/Cntr=0.3,0.1

Type RM Length L Ch R = 1 ,100885. ,480,480,480
BEGIN DESCRIPTION:
4800
END DESCRIPTION:
#Sta/Elev= 30
       0 1432.26   281.9 1428.36   743.7 1423.86   748.1 1422.46  1522.3 1420.06
  1680.5 1419.36    2301 1418.96  2464.6 1419.06  2495.6 1418.96  2525.5 1419.16
  2544.3 1419.46  2554.7 1419.86  2583.8 1418.36  2592.9 1417.36  2641.6 1415.56
  2671.2 1418.16  2690.3 1423.66  2700.4 1426.16  2729.5 1423.46  2738.9 1422.06
  2758.6 1420.76  2783.7 1420.16  3079.2 1419.26  3079.6 1418.96  3545.4 1417.96
    4500 1422.56    4800 1426.56    4940 1430.56    5100 1434.56    5200 1438.56
#Mann= 3 , 0 , 0
       0     .03       0  2554.7    .035       0  2700.4     .03       0
Bank Sta=2554.7,2700.4
XS Rating Curve= 0 ,0
Exp/Cntr=0.3,0.1

Type RM Length L Ch R = 1 ,100405. ,505,505,505
BEGIN DESCRIPTION:
4700
WEST:  Measured 600 feet back from zero to obtain 1428 ft elevation.  Added 600 ft constant to all stations. (RCFCD photo maps)
END DESCRIPTION:
#Sta/Elev= 29
       0 1430.56     600 1426.36  1097.5 1422.26  1564.3 1419.46  1744.2 1419.26
  2497.8 1419.06  2520.3 1419.16    2702 1418.56  2714.3 1418.56  2731.1 1418.76
  2760.3 1419.26  2762.8 1419.36  2789.5 1418.46  2811.4 1416.16  2818.7 1415.96
  2847.8 1416.16 2859.96 1415.16    2877 1415.86  2906.2 1426.16  2908.4 1426.46
  2956.9 1420.86  2964.5 1420.46  3009.9 1419.96  3431.3 1418.46    4920 1422.56
    5200 1426.56    5340 1430.56    5540 1434.56    5700 1438.56
#Mann= 3 , 0 , 0
       0     .03       0  2762.8    .035       0  2908.4     .03       0
#XS Ineff= 2 , 0
       0    1656 1427.56               0
Permanent Ineff=
       F       F
Bank Sta=2762.8,2908.4
XS Rating Curve= 0 ,0
Exp/Cntr=0.3,0.1

Type RM Length L Ch R = 1 ,99900.  ,510,510,510
BEGIN DESCRIPTION:
4600
WEST:  Measured 310 feet back from zero to obtain 1428 ft elevation.  Added 310 constant to all stations. (RCFCD photo maps)
END DESCRIPTION:
#Sta/Elev= 30
       0 1430.56     310 1425.46   745.1 1422.96  1210.7 1419.86  1676.4 1418.86
    1757 1418.76    2142 1419.06  2538.3 1419.06  2607.7 1417.46  2640.7 1418.56
    2695 1418.46    2724 1418.86  2733.6 1419.46  2753.1 1420.26  2782.4 1415.96
  2811.4 1415.86  2831.3 1414.46  2840.5 1414.26  2869.6 1420.56  2880.1 1423.06
  2898.7 1424.66  2927.8 1418.56  2979.8 1418.16  3073.3 1418.16  3319.6 1417.26
    4310 1422.56    4590 1426.56    4810 1430.56    4990 1434.56    5210 1438.56
#Mann= 3 , 0 , 0
       0     .03       0  2753.1    .035       0  2898.7     .03       0
#XS Ineff= 2 , 0
       0    1902 1427.56               0
Permanent Ineff=
       F       F
Bank Sta=2753.1,2898.7
XS Rating Curve= 0 ,0
Exp/Cntr=0.3,0.1

Type RM Length L Ch R = 1 ,99390.  ,490,490,490
BEGIN DESCRIPTION:
4500
WEST:  Measure back 310 feet to obtain 1428 ft elevation.  Added 310 constant to all stations. (RCFCD photo maps)
END DESCRIPTION:
#Sta/Elev= 26
       0 1430.56     310 1426.36   456.8 1424.56  1029.7 1420.56  1389.8 1419.56
  1856.4 1419.26  2322.9 1419.16  2738.1 1418.76  2760.3 1418.86  2778.4 1420.16
  2789.5 1420.56  2818.6 1416.66  2847.8 1415.76  2875.6 1414.46    2877 1414.46
  2924.1 1424.76  2935.3 1425.36  2964.4 1418.56  2972.7 1418.46  3022.7 1418.26
  3051.9 1418.26  3072.4 1417.16    3256 1418.16    4310 1422.56    4510 1430.56
    4910 1438.56
#Mann= 3 , 0 , 0
       0     .03       0  2789.5    .035       0  2935.3     .03       0
#XS Ineff= 2 , 0
       0    2053 1427.56               0
Permanent Ineff=
       F       F
Bank Sta=2789.5,2935.3
XS Rating Curve= 0 ,0
Exp/Cntr=0.3,0.1

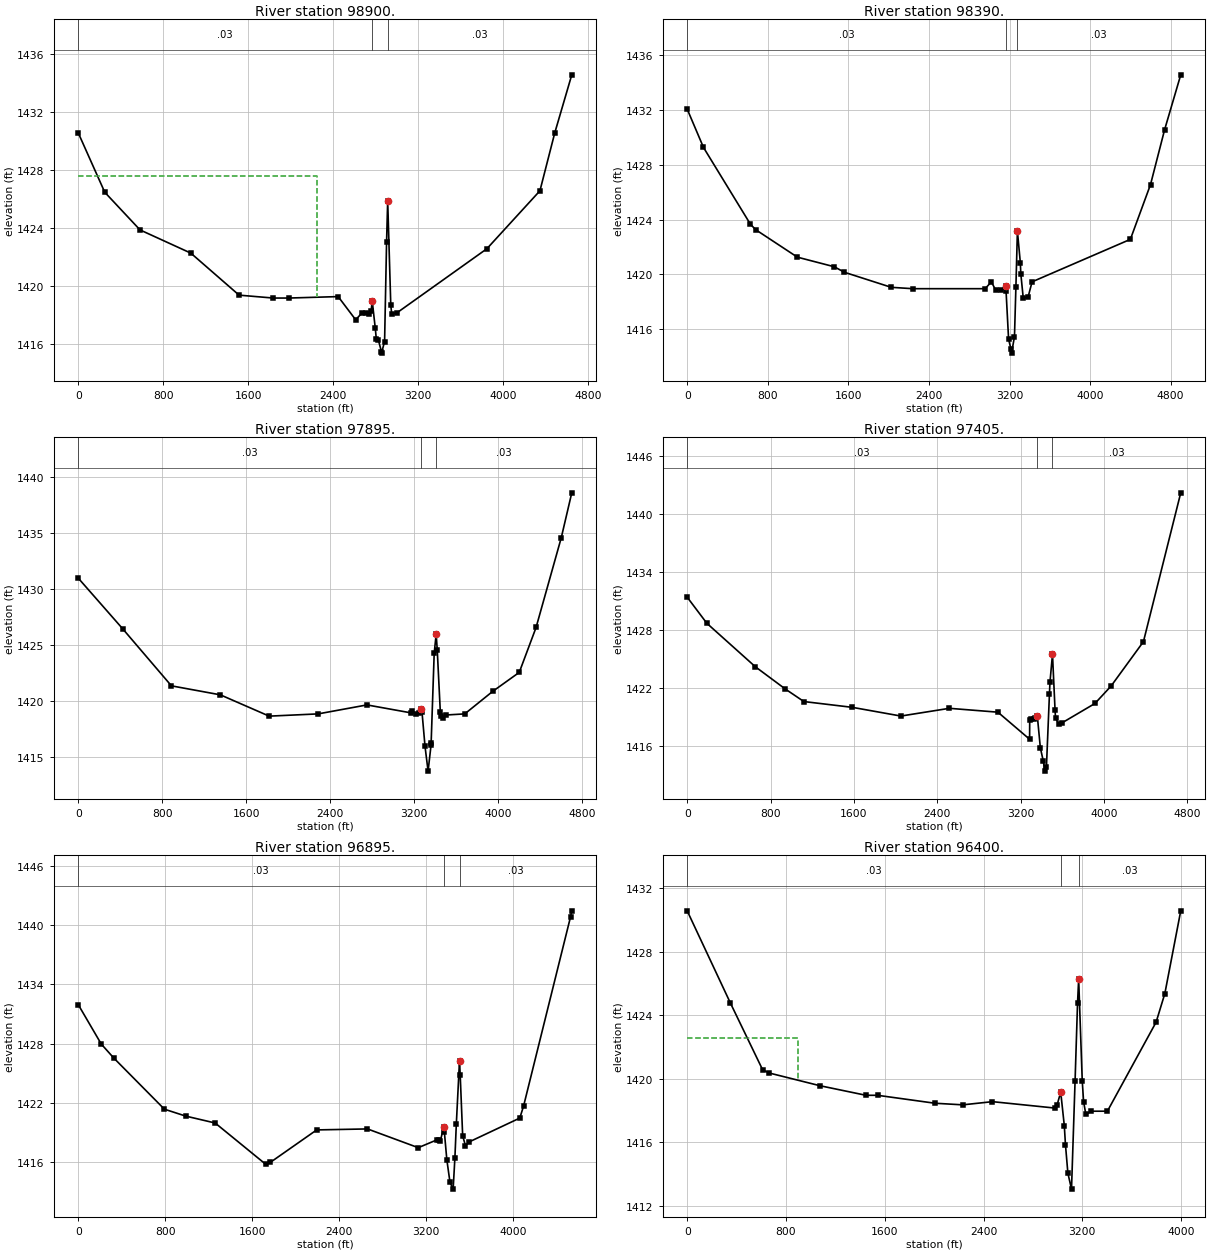
Type RM Length L Ch R = 1 ,98900.  ,510,510,510
BEGIN DESCRIPTION:
4400
WEST: Measured back 250 feet from zero to obtain 1428 contour interval.  Added 250 constant to all stations...
(RCFCD photo maps)
END DESCRIPTION:
#Sta/Elev= 29
       0 1430.56     250 1426.46   582.4 1423.86  1060.8 1422.26  1515.7 1419.36
  1837.4 1419.16  1982.4 1419.16  2449.1 1419.26    2614 1417.66    2677 1418.16
  2711.1 1418.16  2740.7 1418.06  2759.7 1418.26  2769.9 1418.96    2799 1417.06
  2808.2 1416.36  2828.2 1416.26  2856.7 1415.46  2857.4 1415.36  2886.5 1416.16
  2905.3 1423.06  2915.7 1425.86  2944.9 1418.66  2953.8 1418.06  3006.6 1418.16
    3850 1422.56    4350 1426.56    4490 1430.56    4650 1434.56
#Mann= 3 , 0 , 0
       0     .03       0  2769.9    .035       0  2915.7     .03       0
#XS Ineff= 2 , 0
       0    2254 1427.56               0
Permanent Ineff=
       F       F
Bank Sta=2769.9,2915.7
XS Rating Curve= 0 ,0
Exp/Cntr=0.3,0.1

Type RM Length L Ch R = 1 ,98390.  ,495,495,495
BEGIN DESCRIPTION:
4300
END DESCRIPTION:
#Sta/Elev= 30
       0 1432.06   161.9 1429.26     628 1423.66   680.8 1423.26    1094 1421.26
  1460.5 1420.56    1560 1420.16    2026 1419.06  2240.1 1418.96    2958 1418.96
  3019.7 1419.46  3062.6 1418.86  3117.2 1418.86  3161.9 1419.16  3165.9 1418.76
    3191 1415.26  3214.7 1414.56  3220.1 1414.26  3249.3 1415.46  3263.4 1419.06
  3278.4 1423.16  3307.5 1420.86  3312.1 1420.06  3336.6 1418.26  3384.7 1418.36
    3424 1419.46    4400 1422.56    4600 1426.56    4740 1430.56    4900 1434.56
#Mann= 3 , 0 , 0
       0     .03       0  3161.9    .035       0  3278.4     .03       0
Bank Sta=3161.9,3278.4
XS Rating Curve= 0 ,0
Exp/Cntr=0.3,0.1

Type RM Length L Ch R = 1 ,97895.  ,490,490,490
BEGIN DESCRIPTION:
4200
END DESCRIPTION:
#Sta/Elev= 30
       0 1430.96     422 1426.46   887.6 1421.36  1353.1 1420.56  1818.7 1418.66
  2284.2 1418.86  2749.8 1419.66  3164.4 1418.96  3182.5 1419.16  3213.2 1418.86
  3244.4 1418.96  3262.1 1419.26  3273.5 1419.06  3302.6 1415.96  3331.7 1413.76
  3359.8 1416.06  3360.8 1416.26  3389.9 1424.26  3408.7 1425.96    3419 1424.56
  3448.1 1419.06  3457.5 1418.66  3477.2 1418.46    3500 1418.76  3680.9 1418.86
  3946.2 1420.86    4200 1422.56    4360 1426.56    4600 1434.56    4700 1438.56
#Mann= 3 , 0 , 0
       0     .03       0  3262.1    .035       0  3408.7     .03       0
Bank Sta=3262.1,3408.7
XS Rating Curve= 0 ,0
Exp/Cntr=0.3,0.1

Type RM Length L Ch R = 1 ,97405.  ,510,510,510
BEGIN DESCRIPTION:
4100
END DESCRIPTION:
#Sta/Elev= 30
       0 1431.36   188.7 1428.66   654.3 1424.16   941.4 1421.86  1119.9 1420.56
  1585.4 1419.96    2051 1419.06  2516.6 1419.86  2982.2 1419.46  3286.4 1416.66
  3287.4 1418.66  3302.3 1418.76  3331.4 1418.76  3335.2 1418.86  3360.5 1419.06
  3389.6 1415.76  3418.7 1414.36  3432.9 1413.36  3447.8 1413.76  3476.9 1421.36
  3481.8 1422.56    3506 1425.46  3530.7 1419.66  3535.1 1418.86  3564.2 1418.26
  3598.3 1418.36  3913.3 1420.36    4068 1422.16  4378.9 1426.76  4736.9 1442.16
#Mann= 3 , 0 , 0
       0     .03       0  3360.5    .035       0    3506     .03       0
Bank Sta=3360.5,3506
XS Rating Curve= 0 ,0
Exp/Cntr=0.3,0.1

Type RM Length L Ch R = 1 ,96895.  ,495,495,495
BEGIN DESCRIPTION:
4000
END DESCRIPTION:
#Sta/Elev= 30
       0 1431.96   211.9 1427.96   325.5 1426.56   792.2 1421.36   988.3 1420.66
  1258.9 1419.96  1725.6 1415.76  1764.6 1415.96  2192.3 1419.26  2659.1 1419.36
  3125.8 1417.46  3299.1 1418.26  3317.3 1418.26  3329.9 1418.16  3359.1 1419.56
  3365.8 1419.06  3388.3 1416.26  3417.4 1413.96  3446.6 1413.26  3462.8 1416.46
  3475.8 1419.86    3505 1426.26  3511.3 1424.86  3534.1 1418.66  3559.9 1417.66
  3596.7 1418.06  4059.2 1420.46  4093.6 1421.66  4525.9 1440.86    4537 1441.46
#Mann= 3 , 0 , 0
       0     .03       0  3359.1    .035       0    3505     .03       0
Bank Sta=3359.1,3505
XS Rating Curve= 0 ,0
Exp/Cntr=0.3,0.1

Type RM Length L Ch R = 1 ,96400.  ,500,500,500
BEGIN DESCRIPTION:
3900
WEST:  Measured back 350 feet to obtain 1428 ft elevation.
Added 350 feet constant to all stations.
Measured 50 feet from station 3946.9 with an elevation of 1426 to obtain an elevation of 1428 (RCFCD photo maps)
END DESCRIPTION:
#Sta/Elev= 28
       0 1430.56     350 1424.76   611.2 1420.56   665.2 1420.36  1076.5 1419.56
  1448.3 1418.96  1541.8 1418.96    2007 1418.46  2231.3 1418.36  2472.3 1418.56
  2974.9 1418.16  2995.8 1418.36  3024.9 1419.16  3053.9 1417.06  3063.3 1415.86
    3083 1414.06  3112.3 1413.06  3141.2 1419.86  3161.2 1424.76  3170.3 1426.26
  3199.3 1419.86  3210.2 1418.56  3228.4 1417.76  3272.9 1417.96  3402.9 1417.96
  3797.5 1423.56  3868.2 1425.36  3996.9 1430.56
#Mann= 3 , 0 , 0
       0     .03       0  3024.9    .035       0  3170.3     .03       0
#XS Ineff= 2 , 0
       0     900 1422.56               0
Permanent Ineff=
       F       F
Bank Sta=3024.9,3170.3
XS Rating Curve= 0 ,0
Exp/Cntr=0.3,0.1

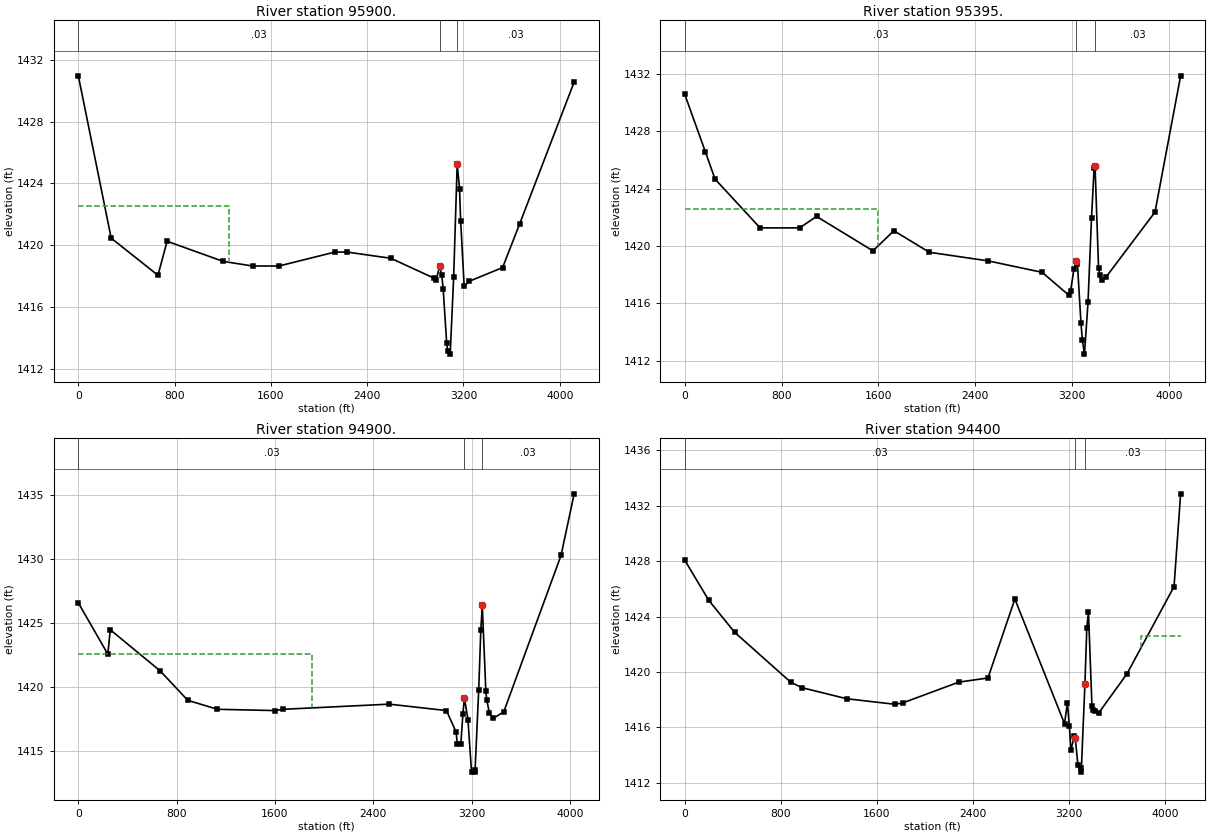
Type RM Length L Ch R = 1 ,95900.  ,505,505,505
BEGIN DESCRIPTION:
3800
END DESCRIPTION:
#Sta/Elev= 27
       0 1430.96     273 1420.46   661.7 1418.06   737.7 1420.26  1202.3 1418.96
  1447.8 1418.66  1666.9 1418.66  2131.6 1419.56    2234 1419.56  2596.2 1419.16
  2959.3 1417.86  2973.7 1417.76  3002.8 1418.66  3020.2 1418.06  3031.8 1417.16
  3060.8 1413.66  3069.3 1413.16  3089.9 1412.96  3118.9 1417.96    3148 1425.26
  3167.6 1423.66    3177 1421.56    3206 1417.36  3244.6 1417.66  3525.5 1418.56
  3665.9 1421.36    4120 1430.56
#Mann= 3 , 0 , 0
       0     .03       0  3002.8    .035       0    3148     .03       0
#XS Ineff= 2 , 0
       0    1250 1422.56               0
Permanent Ineff=
       F       F
Bank Sta=3002.8,3148
XS Rating Curve= 0 ,0
Exp/Cntr=0.3,0.1

Type RM Length L Ch R = 1 ,95395.  ,495,495,495
BEGIN DESCRIPTION:
3700
WEST:  Measured back 250 feet from zero to obtain 1428 ft elevation.  Added 250 constant to all stations.  Added station 170 for elevation 1424 (RCFCD photo maps)
END DESCRIPTION:
#Sta/Elev= 29
       0 1430.56     170 1426.56     250 1424.66   622.4 1421.26   949.2 1421.26
  1088.6 1422.06  1554.8 1419.66  1727.9 1421.06    2021 1419.56  2506.7 1418.96
  2953.4 1418.16  3174.9 1416.56  3188.1 1416.86  3215.6 1418.36  3236.8 1418.96
  3244.7 1418.76  3273.9 1414.66  3285.5 1413.46    3303 1412.46  3332.2 1416.06
  3361.3 1421.96  3382.8 1425.46  3390.4 1425.56  3419.6 1418.46  3431.5 1417.96
  3448.7 1417.66  3483.7 1417.86  3885.8 1422.36  4097.7 1431.86
#Mann= 3 , 0 , 0
       0     .03       0  3236.8    .035       0  3390.4     .03       0
#XS Ineff= 2 , 0
       0    1600 1422.56               0
Permanent Ineff=
       F       F
Bank Sta=3236.8,3390.4
XS Rating Curve= 0 ,0
Exp/Cntr=0.3,0.1

Type RM Length L Ch R = 1 ,94900.  ,500,500,500
BEGIN DESCRIPTION:
3600
END DESCRIPTION:
#Sta/Elev= 29
       0 1426.56     240 1422.56     260 1424.46   665.4 1421.26   890.7 1418.96
  1131.5 1418.26  1597.7 1418.16  1669.5 1418.26  2530.1 1418.66  2996.3 1418.16
  3075.6 1416.46  3083.6 1415.56  3112.8 1415.56  3129.8 1417.86  3141.9 1419.16
    3171 1417.46  3200.2 1413.36  3227.2 1413.36  3229.3 1413.56  3258.5 1419.76
  3275.8 1424.46  3287.6 1426.36  3316.7 1419.66  3324.5 1418.96  3345.9 1417.96
  3378.3 1417.56  3462.4 1418.06  3928.6 1430.26  4035.4 1435.06
#Mann= 3 , 0 , 0
       0     .03       0  3141.9    .035       0  3287.6     .03       0
#XS Ineff= 2 , 0
       0    1900 1422.56               0
Permanent Ineff=
       F       F
Bank Sta=3141.9,3287.6
XS Rating Curve= 0 ,0
Exp/Cntr=0.3,0.1

Type RM Length L Ch R = 1 ,94400   ,480,480,480
BEGIN DESCRIPTION:
3500
END DESCRIPTION:
#Sta/Elev= 30
       0 1428.06   200.5 1425.16   415.1 1422.86   882.1 1419.26   975.6 1418.86
  1349.1 1418.06  1750.8 1417.66  1816.1 1417.76    2283 1419.26  2525.9 1419.56
    2750 1425.26  3163.8 1416.26  3187.9 1417.76  3204.2 1416.06  3217.1 1414.36
  3246.2 1415.36  3252.6 1415.26  3275.4 1413.26  3301.1 1412.76  3304.6 1413.06
  3333.8 1419.16  3349.5 1423.16    3363 1424.36  3392.2 1417.56    3398 1417.26
  3421.3 1417.16  3450.8 1417.06    3684 1419.86  4076.2 1426.16  4131.1 1432.86
#Mann= 3 , 0 , 0
       0     .03       0  3252.6    .035       0  3333.8     .03       0
#XS Ineff= 2 , 0
       0    2800 1422.56    3800       0 1422.56
Permanent Ineff=
       F       F
Bank Sta=3252.6,3333.8
XS Rating Curve= 0 ,0
Exp/Cntr=0.3,0.1