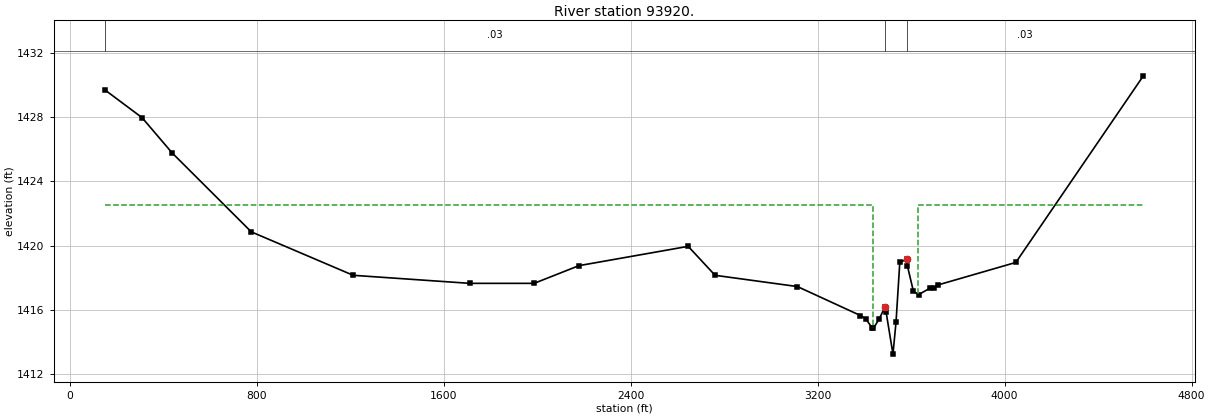
HEC-RAS study RamonaFlowControl.prj: Ramona Flow Control Rating Curve

--- RamonaFlowControl.g05 (geometry) --- (continued)

Type RM Length L Ch R = 1 ,93920.  ,8440,8890,7740
BEGIN DESCRIPTION:
copied 3300
END DESCRIPTION:
#Sta/Elev= 30
  153.35 1429.66  310.05 1427.96  439.15 1425.76  777.35 1420.86 1213.15 1418.16
 1711.75 1417.66 1987.25 1417.66 2178.95 1418.76 2646.25 1419.96 2761.25 1418.16
 3113.45 1417.46 3383.15 1415.66 3405.45 1415.46 3434.65 1414.86 3438.55 1414.86
 3463.85 1415.46 3486.95 1416.16 3493.05 1415.86 3522.25 1413.26 3535.35 1415.26
 3551.45 1418.96 3580.65 1419.16 3583.75 1418.76 3609.85 1417.16 3632.05 1416.96
 3680.45 1417.36 3697.45 1417.36 3714.75 1417.56 4047.85 1418.96 4593.35 1430.56
#Mann= 3 , 0 , 0
  153.35     .03       0 3486.95    .035       0 3580.65     .03       0
#XS Ineff= 2 , 0
       0    3437 1422.56    3631       0 1422.56
Permanent Ineff=
       F       F
Bank Sta=3486.95,3580.65
XS Rating Curve= 0 ,0
Exp/Cntr=0.3,0.1
LCMann Table=0

Chan Stop Cuts=-1
Use User Specified Reach Order=0
Composite Channel Slope=5